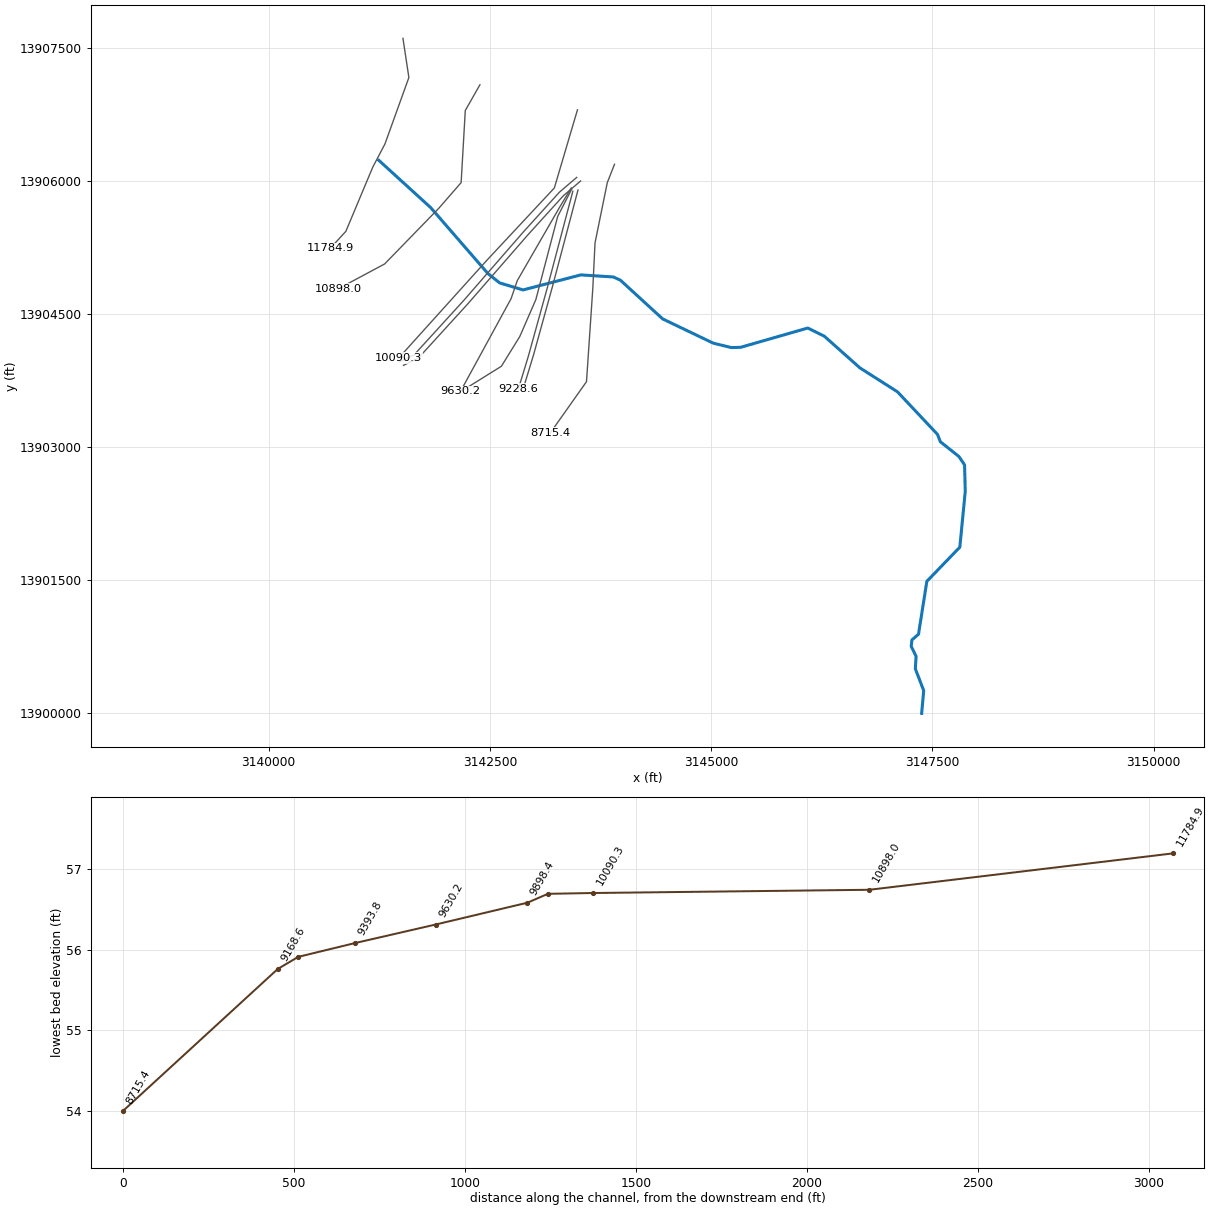
--- P133-00-00.PRJ (project) ---

Proj Title=P133-00-00
Current Plan=p02
Default Exp/Contr=.3,.1
English Units
Geom File=g01
Flow File=f01
Flow File=f02
Plan File=p01
Plan File=p02
Y Axis Title=Elevation
X Axis Title(PF)=Main Channel Distance
X Axis Title(XS)=Station
BEGIN DESCRIPTION:
Greens Bayou Watershed
Tributary 20.88 to Greens Bayou
HCFCD Unit P133-00-00
Flood Hazard Model
10, 2, 1, 0.2% Event
Filename P133-00-00.prj
Prepared by:  Watershed Concepts  Date:
Reviewed by:                      Date:
STATUS FINAL
END DESCRIPTION:
DSS Export Rating Curves= 0
DSS Export Rating Curve Sorted= 0
DSS Export Volume Flow Curves= 0
DXF OffsetX= 0
DXF OffsetY= 0
DXF ScaleX= 1
DXF ScaleY= 10

--- P133-00-00.p02 (plan) ---

Plan Title=Floodway
Version=Version 3.0.1  Mar 2001
Short Identifier=Floodway0607
Geom File=g01
Flow File=f02
Subcritical Flow
K Sum by GR= 0
Std Step Tol= 0.01
Critical Tol= 0.01
Num of Std Step Trials= 20
Max Error Tol= 0.3
Flow Tol Ratio= 0.001
Split Flow NTrial= 30
Split Flow Tol= 0.02
Split Flow Ratio= 0.02
Log Output Level= 0
Friction Slope Method= 1
Unsteady Friction Slope Method= 2
Parabolic Critical Depth
Global Vel Dist= 0 , 0 , 0
Global Log Level= 0
CheckData=True
Encroach Param=-1 ,0,0, 2
Encroach River=P133-00-00
Encroach Reach=Reach - 1
Encroach Node=11784.9
       1    4980    5030
Encroach Node=10898.0
       1    4950    5175
Encroach Node=10090.3
       1    4949    5200
Encroach Node=9958.4
       1    4900    5150
Encroach Node=9928.4
       1    4900    5150
Encroach Node=9898.4
       1    4900    5150
Encroach Node=9630.2
       1    4970    5080
Encroach Node=9393.8
       1    4945 5039.68
Encroach Node=9228.6
       1 4982.31 5039.68
Encroach Node=9198.6
       1 4982.31 5039.68
Encroach Node=9168.6
       1 4982.31 5039.68
Encroach Node=8715.4
       1    4730    5200
Encroach Node=8220.5
       1    4900    5100
Encroach Node=8124.0
       1    4890    5110
Encroach Node=8088.0
       1    4890    5110
Encroach Node=8052.0
       1    4890    5110
Encroach Node=8025.2
       1    4890    5110
Encroach Node=8014.2
       1    4890    5110
Encroach Node=8003.2
       1    4890    5110
Encroach Node=7582.4
       1    4955    5045
Encroach Node=7133.7
       1    4930    5025
Encroach Node=6501.9
       1  4980.9    5080
Encroach Node=5972.3
       1    4945    5050
Encroach Node=5280.9
       1    4929  5031.1
Encroach Node=4780.1
       1  4981.2  5031.1
Encroach Node=3708.7
       1  4977.2  5026.8
Encroach Node=2839.4
       1  4983.9  5070.7
Encroach Node=1734.0
       1    4925    5043
Encroach Node=675.7
       1    4800    5125
Encroach Reach=P133-00-00_0007
Encroach Node=11784.9
       1    4980    5030
Encroach Node=10898.0
       1    4950    5175
Encroach Node=10090.3
       1    4949    5200
Encroach Node=9958.4
       1    4900    5150
Encroach Node=9928.4
       1    4900    5150
Encroach Node=9898.4
       1    4900    5150
Encroach Node=9630.2
       1    4970    5080
Encroach Node=9393.8
       1    4945 5039.68
Encroach Node=9228.6
       1 4982.31 5039.68
Encroach Node=9198.6
       1 4982.31 5039.68
Encroach Node=9168.6
       1 4982.31 5039.68
Encroach Node=8715.4
       1    4730    5200
Encroach Node=8220.5
       1    4900    5100
Encroach Node=8124.0
       1    4890    5110
Encroach Node=8088.0
       1    4890    5110
Encroach Node=8052.0
       1    4890    5110
Encroach Node=8025.2
       1    4890    5110
Encroach Node=8014.2
       1    4890    5110
Encroach Node=8003.2
       1    4890    5110
Encroach Node=7582.4
       1    4955    5045
Encroach Node=7133.7
       1    4930    5025
Encroach Node=6501.9
       1  4980.9    5080
Encroach Node=5972.3
       1    4945    5050
Encroach Node=5280.9
       1    4929  5031.1
Encroach Node=4780.1
       1  4981.2  5031.1
Encroach Node=3708.7
       1  4977.2  5026.8
Encroach Node=2839.4
       1  4983.9  5070.7
Encroach Node=1734.0
       1    4925    5043
Encroach Node=675.7
       1    4800    5125
Computation Interval=1HOUR
Output Interval=1HOUR
Run HTab= 0
Run UNet= 0
Run PostProcess= 0
UNET Theta= 1
UNET ZTol= 0.02
UNET ZSATol= 0.1
UNET MxIter= 20
UNET MaxInSteps= 20
UNET DtIC= 0
UNET DtMin= 0
UNET MaxCRTS= 20
UNET WFStab= 2
UNET SFStab= 1
UNET WFX= 1
UNET SFX= 1
UNET Convert EG Bridges=-1
UNET Use Existing IB Tables=-1
Instantaneous Interval=1HOUR
DSS File=dss
Write IC File= 0
Write Velocity= 0
Write Detailed= 0

--- P133-00-00.p01 (plan) ---

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Plan Title=FEMA Effective June 2007
Short Identifier=FEMAeff0607
Geom File=g01
Flow File=f01
Encroach Param=-1 ,0,0, 0

--- P133-00-00.f02 (steady flow) ---

Flow Title= Floodway
Number of Profiles= 2
Profile Names=1PCT_100yr, 1PCTFloodway_100yrFW
River Rch & RM=P133-00-00,P133-00-00_0007,11784.9
    1157    1157
River Rch & RM=P133-00-00,P133-00-00_0007,10898
    1233    1233
River Rch & RM=P133-00-00,P133-00-00_0007,10090.3
    1279    1279
River Rch & RM=P133-00-00,P133-00-00_0007,9630.2
    1322    1322
River Rch & RM=P133-00-00,P133-00-00_0007,9228.6
    1356    1356
River Rch & RM=P133-00-00,P133-00-00_0007,8715.4
    1407    1407
River Rch & RM=P133-00-00,P133-00-00_0007,8025.2
    1471    1471
River Rch & RM=P133-00-00,P133-00-00_0007,7133.7
    1519    1519
River Rch & RM=P133-00-00,P133-00-00_0007,6501.9
    1561    1561
River Rch & RM=P133-00-00,P133-00-00_0007,5972.3
    1617    1617
River Rch & RM=P133-00-00,P133-00-00_0007,5280.9
    1659    1659
River Rch & RM=P133-00-00,P133-00-00_0007,4780.1
    1752    1752
River Rch & RM=P133-00-00,P133-00-00_0007,3708.7
    1832    1832
River Rch & RM=P133-00-00,P133-00-00_0007,2839.4
    1939    1939
River Rch & RM=P133-00-00,P133-00-00_0007,1734
    2046    2046
Boundary for River Rch & Prof#=P133-00-00,P133-00-00_0007, 1
Up Type= 0
Dn Type= 3
Dn Slope= 0.00061
Boundary for River Rch & Prof#=P133-00-00,P133-00-00_0007, 2
Up Type= 0
Dn Type= 3
Dn Slope= 0.00061

--- P133-00-00.f01 (steady flow) ---

Flow Title= FEMA Effective June 2007
Number of Profiles= 4
Profile Names=10PCT_10yr, 2PCT_50yr, 1PCT_100yr, 0.2PCT_500yr
River Rch & RM=P133-00-00,P133-00-00_0007,11784.9
     644     982    1157    1678
River Rch & RM=P133-00-00,P133-00-00_0007,10898
     686    1047    1233    1789
River Rch & RM=P133-00-00,P133-00-00_0007,10090.3
     712    1086    1279    1856
River Rch & RM=P133-00-00,P133-00-00_0007,9630.2
     736    1123    1322    1919
River Rch & RM=P133-00-00,P133-00-00_0007,9228.6
     756    1152    1356    1962
River Rch & RM=P133-00-00,P133-00-00_0007,8715.4
     786    1195    1407    2026
River Rch & RM=P133-00-00,P133-00-00_0007,8025.2
     824    1250    1471    2107
River Rch & RM=P133-00-00,P133-00-00_0007,7133.7
     853    1291    1519    2168
River Rch & RM=P133-00-00,P133-00-00_0007,6501.9
     878    1326    1561    2221
River Rch & RM=P133-00-00,P133-00-00_0007,5972.3
     912    1374    1617    2291
River Rch & RM=P133-00-00,P133-00-00_0007,5280.9
     937    1410    1659    2344
River Rch & RM=P133-00-00,P133-00-00_0007,4780.1
     993    1490    1752    2460
River Rch & RM=P133-00-00,P133-00-00_0007,3708.7
    1042    1558    1832    2558
River Rch & RM=P133-00-00,P133-00-00_0007,2839.4
    1106    1649    1939    2689
River Rch & RM=P133-00-00,P133-00-00_0007,1734
    1172    1741    2046    2821
Boundary for River Rch & Prof#=P133-00-00,P133-00-00_0007, 1
Up Type= 0
Dn Type= 3
Dn Slope= 0.00061
Boundary for River Rch & Prof#=P133-00-00,P133-00-00_0007, 2
Up Type= 0
Dn Type= 3
Dn Slope= 0.00061
Boundary for River Rch & Prof#=P133-00-00,P133-00-00_0007, 3
Up Type= 0
Dn Type= 3
Dn Slope= 0.00061
Boundary for River Rch & Prof#=P133-00-00,P133-00-00_0007, 4
Up Type= 0
Dn Type= 3
Dn Slope= 0.00061

--- P133-00-00.g01 (geometry) ---

Geom Title=P133-00-00 June 2007
Version=Version 3.0.1  Mar 2001

River Reach=P133-00-00      ,P133-00-00_0007
Reach XY= 30
      3141245.53     13906234.56      3141832.25       13905700.
      3142477.75       13904957.      3142610.75       13904851.
        3142875.       13904772.       3143527.6     13904941.56
       3143893.7     13904918.34      3143974.07     13904882.63
      3144451.93     13904445.17      3145022.34      13904171.9
      3145226.62     13904121.49      3145332.75     13904124.14
        3146092.       13904342.       3146278.5       13904250.
        3146681.       13903892.      3147105.25       13903622.
       3147557.1     13903142.05      3147590.28     13903057.84
      3147799.53     13902891.97      3147863.33     13902797.55
      3147870.99     13902498.97      3147809.74     13901868.66
      3147437.16     13901483.32      3147342.74     13900886.18
      3147268.74     13900822.38       3147260.3     13900749.81
       3147315.5       13900637.      3147307.02     13900495.74
      3147401.44     13900250.75      3147378.47     13899993.01

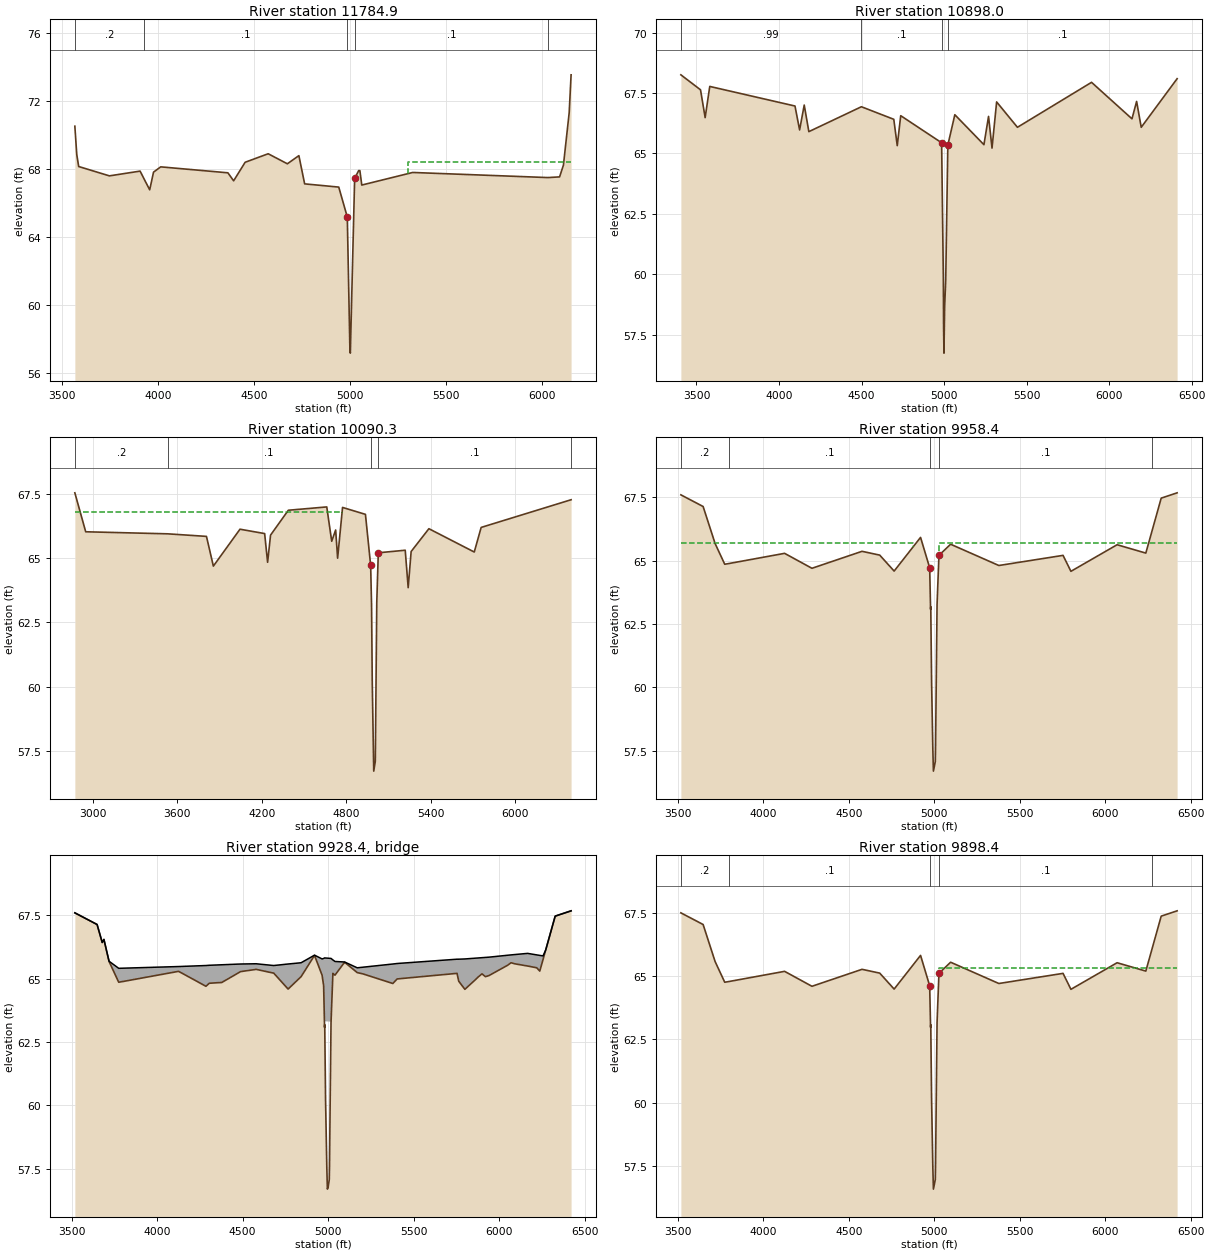
Type RM Length L Ch R = 1 ,11784.9 ,1055.8,886.9,753.3
BEGIN DESCRIPTION:
Cross Section 11784.9
END DESCRIPTION:
XS GIS Cut Line= 6
        3141518.     13907611.42      3141585.01     13907169.12
      3141314.25     13906418.63      3141176.73     13906157.34
      3140872.99     13905433.04      3140696.72     13905241.88
#Sta/Elev= 30
  3565.1   70.53  3575.1   68.86  3585.1   68.16  3745.1   67.61  3905.1   67.89
  3924.5   67.46  3955.1   66.79  3975.1   67.83  4012.5   68.14  4362.5   67.79
  4392.5   67.32  4452.5   68.41  4572.5   68.91  4672.5   68.32  4732.5    68.8
  4762.5   67.14  4940.3   66.95  4984.8   65.19  4998.4    57.4  5000.6   57.19
  5023.1   67.46  5044.1   67.92  5050.3   67.92  5060.3   67.07  5325.6   67.81
  6030.2   67.51    6091   67.55    6111   68.24    6141   71.32    6151   73.55
#Mann= 5 , 1 , 0
  3565.1      .2       0  3924.5      .1       0  4984.8     .04       0
  5023.1      .1       0  6030.2      .2       0
#XS Ineff= 2 , 0
       0    4730    68.4    5300       0    68.4
Permanent Ineff=
       F       F
Bank Sta=4984.8,5023.1
XS Rating Curve= 0
Exp/Cntr=.3,.1

Type RM Length L Ch R = 1 ,10898.0 ,828,807.7,804.5
BEGIN DESCRIPTION:
Cross Section 10898.0
END DESCRIPTION:
XS GIS Cut Line= 6
      3142388.02     13907087.63      3142222.34     13906797.28
      3142175.37     13905983.08      3141923.23     13905693.74
      3141311.47     13905065.45      3140786.52     13904784.37
#Sta/Elev= 30
  3405.7   68.25  3524.7   67.63  3552.7   66.48  3580.7   67.77    4097   66.96
    4125   65.97    4153      67    4181    65.9  4499.4   66.93  4695.6   66.41
  4716.6   65.32  4737.6   66.56  4985.4   65.44  4995.8   59.89  4997.4   57.76
  4999.6   56.74  5003.5   58.61  5010.3   59.78    5023   65.34  5065.4    66.6
  5241.7   65.36  5269.7   66.53  5290.7   65.22  5318.7   67.13  5444.7   66.08
  5893.7   67.94  6138.7   66.43  6166.7   67.15  6194.7   66.08  6412.2   68.09
#Mann= 4 , 1 , 0
  3405.7     .99       0  4499.4      .1       0  4985.4     .04       0
    5023      .1       0
#XS Ineff= 2 , 0
       0    3880    67.3    5816       0    67.3
Permanent Ineff=
       F       F
Bank Sta=4985.4,5023
XS Rating Curve= 0
Exp/Cntr=.3,.1

Type RM Length L Ch R = 1 ,10090.3 ,127.8,131.9,140.1
BEGIN DESCRIPTION:
Cross Section 10090.3-Interpolated
END DESCRIPTION:
XS GIS Cut Line= 5
       3143489.8      13906804.7      3143228.35     13905922.45
      3142467.42     13905108.12      3142310.85     13904935.07
      3141470.31     13904003.88
#Sta/Elev= 30
  2873.8   67.56  2950.8   66.04  3532.5   65.96    3808   65.86    3857    64.7
    4046   66.14    4221   65.97    4242   64.85    4263   65.91    4389   66.88
    4662   67.01    4697   65.67    4725   66.11    4739   65.01    4774   66.99
  4936.5   66.72  4973.5   64.73  4979.9   63.19  4984.8   60.21  4995.4    56.7
  5006.5   57.08  5016.9   63.28  5027.7   65.22  5218.9   65.32  5239.9   63.86
  5260.9   65.27  5386.9   66.16  5708.9   65.25  5757.9   66.21  6396.3   67.29
#Mann= 5 , 1 , 0
  2873.8      .2       0  3532.5      .1       0  4973.5     .04       0
  5027.7      .1       0  6396.3      .2       0
#XS Ineff= 2 , 0
       0    4770    66.8               0
Permanent Ineff=
       F       F
Bank Sta=4973.5,5027.7
XS Rating Curve= 0
Exp/Cntr=.5,.3

Type RM Length L Ch R = 1 ,9958.4  ,60,60,60
BEGIN DESCRIPTION:
Upstream Section of Bridge/Culvert/Weir
END DESCRIPTION:
XS GIS Cut Line= 6
      3143480.44      13906041.3      3143285.46     13905874.82
      3142880.38      13905428.4      3142206.63     13904655.44
      3141644.47     13904039.55      3141479.13     13903961.01
#Sta/Elev= 30
  3518.8    67.6  3648.8   67.14  3718.8   65.68  3775.2   64.86  3801.4   64.89
  4125.2   65.29  4285.2    64.7    4578   65.37  4681.5   65.22  4765.7   64.59
  4920.2   65.92  4973.5   64.72  4978.8   63.08  4979.9   63.18  4984.8    60.2
  4992.1   57.53  4995.4   56.69  5006.5   57.07  5007.9   57.65  5016.7   63.27
  5027.7   65.21    5096   65.65    5378   64.81  5753.4   65.21  5799.4   64.58
  6069.4   65.63  6237.3    65.3  6271.8   66.13  6327.3   67.47  6420.4   67.68
#Mann= 5 , 1 , 0
  3518.8      .2       0  3801.4      .1       0  4973.5     .04       0
  5027.7      .1       0  6271.8      .2       0
#XS Ineff= 2 , 0
       0    4878    65.7    5027       0    65.7
Permanent Ineff=
       F       F
Bank Sta=4973.5,5027.7
XS Rating Curve= 0
Exp/Cntr=.5,.3

Type RM Length L Ch R = 3 ,9928.4  ,,,
BEGIN DESCRIPTION:
OLD HUMBLE ROAD
Structure ID: P33-9,,,,
END DESCRIPTION:
Bridge Culvert--1,0,-1,-1, 0
Deck Dist Width WeirC Skew NumUp NumDn MinLoCord MaxHiCord MaxSubmerge Is_Ogee
10,40,2.6,0, 41, 41, , , .95, 0, 1,1,,
  3518.8  3648.8  3678.8  3688.8  3718.8  3775.2  4125.2  4285.2  4305.2    4378
    4488    4578  4681.5  4765.7  4841.8  4920.2  4964.7  4973.5  4978.8  4978.9
 5016.89  5027.7  5039.9    5096  5169.9    5378  5403.4  5753.4  5763.4  5799.4
  5899.4  5919.4  5939.4  6069.4  6166.1  6219.4  6237.3  6256.1  6271.8  6327.3
  6420.4
    67.6   67.14   66.43   66.55   65.69   65.41   65.48   65.52   65.53   65.55
   65.58   65.59   65.52   65.58   65.63   65.93   65.78    65.8   65.82   65.82
    65.8   65.74   65.68   65.66   65.43   65.58    65.6   65.77   65.77   65.78
   65.83   65.84   65.85   65.94      66   65.94   65.92    65.9   66.13   67.47
   67.68
    67.6   67.14   66.43   66.55   65.68   64.86   65.29    64.7   64.82   64.85
   65.28   65.37   65.22   64.59   65.08   65.92   65.13   64.72   63.08   63.32
    63.3   65.21   65.14   65.65   65.24   64.81   64.99   65.21    64.9   64.58
   65.19   65.08   65.12   65.63    65.5   65.43    65.3   65.75   66.13   67.47
   67.68
  3518.8  3648.8  3678.8  3688.8  3718.8  3775.2  4125.2  4285.2  4305.2    4378
    4488    4578  4681.5  4765.7  4841.8  4920.2  4964.7  4973.5  4978.8  4978.9
 5016.89  5027.7  5039.9    5096  5169.9    5378  5403.4  5753.4  5763.4  5799.4
  5899.4  5919.4  5939.4  6069.4  6166.1  6219.4  6237.3  6256.1  6271.8  6327.3
  6420.4
    67.6   67.14   66.43   66.55   65.69   65.41   65.48   65.52   65.53   65.55
   65.58   65.59   65.52   65.58   65.63   65.93   65.78    65.8   65.82   65.82
    65.8   65.74   65.68   65.66   65.43   65.58    65.6   65.77   65.77   65.78
   65.83   65.84   65.85   65.94      66   65.94   65.92    65.9   66.13   67.47
   67.68
    67.5   67.04   66.33   66.45   65.58   64.76   65.19    64.6   64.72   64.75
   65.18   65.27   65.12   64.49   64.98   65.82   65.03   64.62   62.98   63.22
    63.2   65.11   65.04   65.55   65.14   64.71   64.89   65.11    64.8   64.48
   65.09   64.98   65.02   65.53    65.4   65.33    65.2   65.65   66.03   67.37
   67.58
BR Coef= 1 , 1 , 0 ,1.25, 0 ,,,.8,0,2,0,
WSPro=,,,, 1 ,,,, 0 ,,,, 0 ,,,,-1 ,-1 ,-1 , 0 , 0 , 0 , 0 , 0
BR U #Sta/Elev= 78
  3518.8    67.6  3648.8   67.14  3678.8   66.43  3688.8   66.55  3701.4   66.18
  3718.8   65.68  3775.2   64.86  3801.4   64.89  4125.2   65.29  4201.4   65.01
  4285.2    64.7  4305.2   64.82    4378   64.85    4488   65.28  4571.4   65.36
    4578   65.37  4652.5   65.26  4681.5   65.22  4765.7   64.59  4841.8   65.08
  4918.4    65.9  4920.2   65.92  4964.7   65.13 4966.99   65.02  4967.1   65.02
 4967.21   65.01  4973.5   64.72  4977.3   63.54  4978.6   63.14 4978.71   63.11
  4978.8   63.08  4978.9   63.09    4979    63.1  4979.9   63.18  4984.8    60.2
  4992.1   57.53  4995.4   56.69    5000   56.77  5006.5   57.07  5007.9   57.65
    5012   60.36  5016.7   63.27  5016.8   63.29 5016.89    63.3    5017   63.32
  5017.1   63.34  5027.7   65.21 5028.69    65.2  5028.8    65.2 5028.91    65.2
  5030.5   65.19  5039.9   65.14    5096   65.65  5096.1   65.65  5169.9   65.24
  5203.2   65.19    5378   64.81  5403.4   64.99  5546.1   65.08  5753.4   65.21
  5763.4    64.9  5783.4   64.72  5799.4   64.58  5856.1   64.93  5879.4   65.08
  5899.4   65.19  5919.4   65.08  5939.4   65.12  6049.4   65.53  6069.4   65.63
  6089.4   65.59  6166.1    65.5  6219.4   65.43  6237.3    65.3  6256.1   65.75
  6271.8   66.13  6327.3   67.47  6420.4   67.68
BR U #Mann= 5
  3518.8      .2  3801.4      .1  4973.5     .04  5027.7      .1  6271.8      .2
BR U Banks=4973.5,5027.7
BR D #Sta/Elev= 78
  3518.8    67.5  3648.8   67.04  3678.8   66.33  3688.8   66.45  3701.4   66.08
  3718.8   65.58  3775.2   64.76  3801.4   64.79  4125.2   65.19  4201.4   64.91
  4285.2    64.6  4305.2   64.72    4378   64.75    4488   65.18  4571.4   65.26
    4578   65.27  4652.5   65.16  4681.5   65.12  4765.7   64.49  4841.8   64.98
  4918.4    65.8  4920.2   65.82  4964.7   65.03 4966.99   64.92  4967.1   64.92
 4967.21   64.91  4973.5   64.62  4977.3   63.44  4978.6   63.04 4978.71   63.01
  4978.8   62.98  4978.9   62.99    4979      63  4979.9   63.08  4984.8    60.1
  4992.1   57.43  4995.4   56.59    5000   56.67  5006.5   56.97  5007.9   57.55
    5012   60.26  5016.7   63.17  5016.8   63.19 5016.89    63.2    5017   63.22
  5017.1   63.24  5027.7   65.11 5028.69    65.1  5028.8    65.1 5028.91    65.1
  5030.5   65.09  5039.9   65.04    5096   65.55  5096.1   65.55  5169.9   65.14
  5203.2   65.09    5378   64.71  5403.4   64.89  5546.1   64.98  5753.4   65.11
  5763.4    64.8  5783.4   64.62  5799.4   64.48  5856.1   64.83  5879.4   64.98
  5899.4   65.09  5919.4   64.98  5939.4   65.02  6049.4   65.43  6069.4   65.53
  6089.4   65.49  6166.1    65.4  6219.4   65.33  6237.3    65.2  6256.1   65.65
  6271.8   66.03  6327.3   67.37  6420.4   67.58
BR D #Mann= 5
  3518.8      .2  3801.4      .1  4973.5     .04  5027.7      .1  6271.8      .2
BR D Banks=4973.5,5027.7
BC Design=,, 0 ,, 0 ,,,,,,

Type RM Length L Ch R = 1 ,9898.4  ,268.2,268.2,268.2
BEGIN DESCRIPTION:
Downstream Section of Bridge/Culvert/Weir
END DESCRIPTION:
XS GIS Cut Line= 6
       3143525.4     13906001.56      3143330.42     13905835.08
      3142925.34     13905388.66      3142251.59      13904615.7
      3141689.43     13903999.81      3141524.09     13903921.27
#Sta/Elev= 30
  3518.8   67.49  3648.8   67.03  3718.8   65.57  3775.2   64.75  3801.4   64.78
  4125.2   65.18  4285.2   64.59    4578   65.26  4681.5   65.11  4765.7   64.48
  4920.2   65.81  4973.5   64.61  4978.8   62.97  4979.9   63.07  4984.8   60.09
  4992.1   57.42  4995.4   56.58  5006.5   56.96  5007.9   57.54  5016.7   63.16
  5027.7    65.1    5096   65.54    5378    64.7  5753.4    65.1  5799.4   64.47
  6069.4   65.52  6237.3   65.19  6271.8   66.02  6327.3   67.36  6420.4   67.57
#Mann= 5 , 1 , 0
  3518.8      .2       0  3801.4      .1       0  4973.5     .04       0
  5027.7      .1       0  6271.8      .2       0
#XS Ineff= 2 , 0
       0    4878    65.3    5027       0    65.3
Permanent Ineff=
       F       F
Bank Sta=4973.5,5027.7
XS Rating Curve= 0
Exp/Cntr=.5,.3

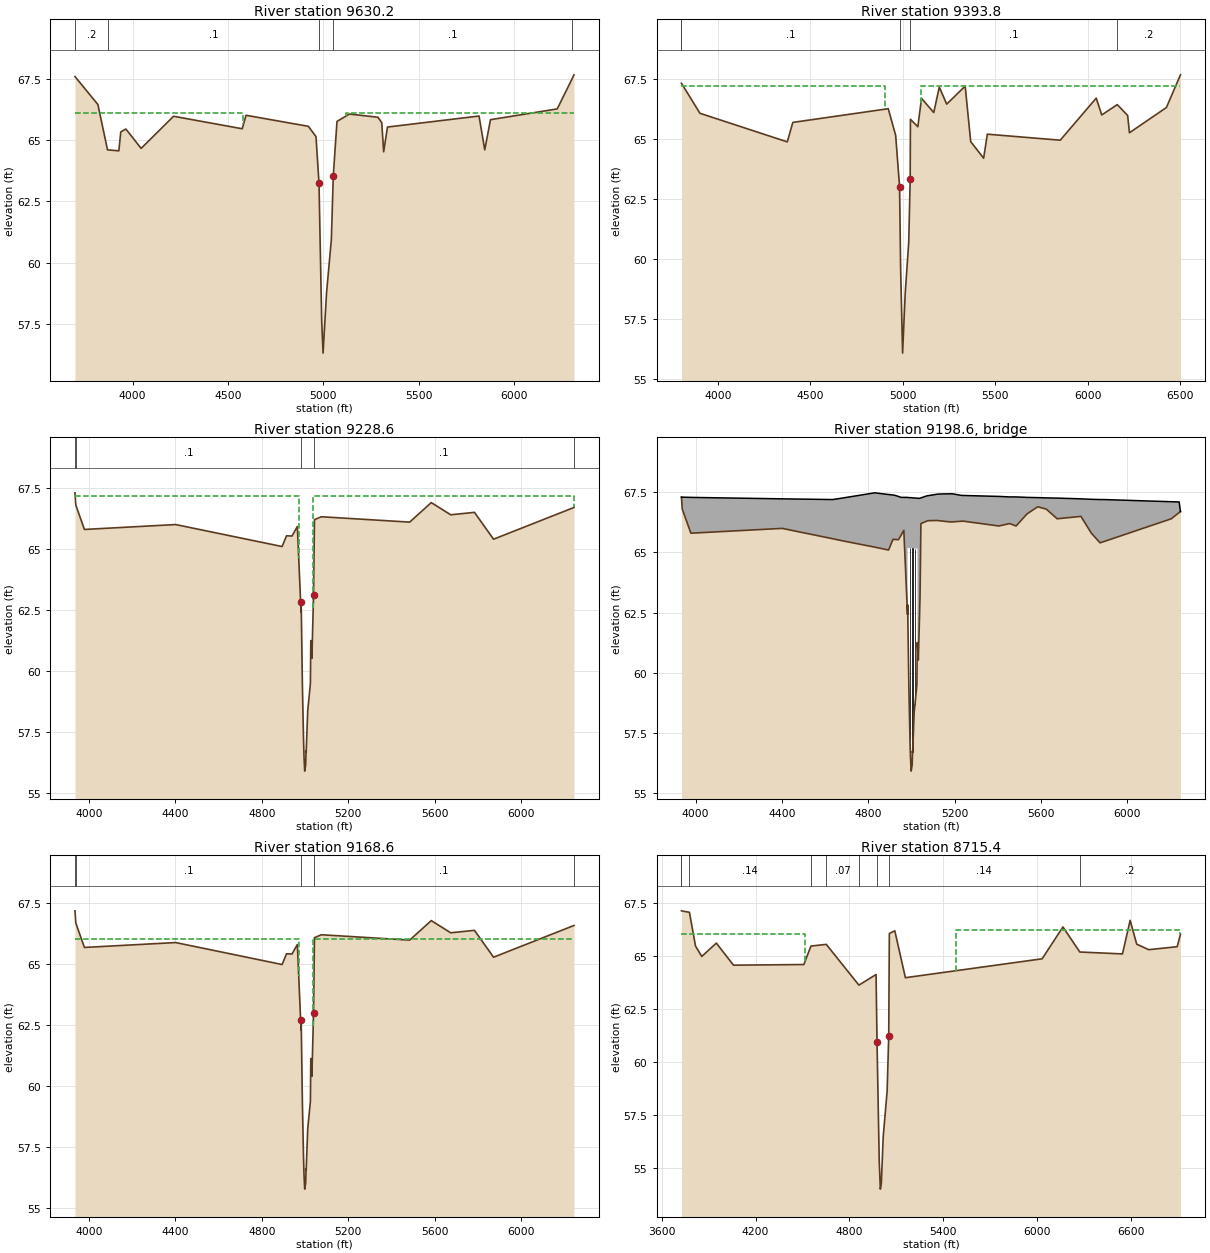
Type RM Length L Ch R = 1 ,9630.2  ,72.6,236.4,278.3
BEGIN DESCRIPTION:
Cross Section 9630.2-Interpolated
END DESCRIPTION:
XS GIS Cut Line= 5
      3143419.48     13905922.34      3143288.02     13905705.22
      3142809.52      13904876.6      3142739.75     13904673.63
      3142169.04     13903628.39
#Sta/Elev= 30
  3697.6   67.59  3817.6   66.45  3868.2    64.6  3927.6   64.56  3937.6   65.33
  3964.4   65.45  4044.4   64.66  4214.4   65.97  4574.4   65.46  4594.4   66.01
  4921.2   65.56  4961.2   65.14  4976.9   63.23  4991.1    57.6  4998.2   56.31
  5016.6   58.79  5041.6   60.93  5051.8   63.54  5071.2   65.76  5135.9   66.06
  5285.9   65.93  5305.9   65.71  5315.9   64.52  5335.9   65.53  5815.9   65.98
  5845.9    64.6  5875.9   65.83  6225.9   66.27  6300.8   67.45  6313.8   67.66
#Mann= 5 , 1 , 0
  3697.6      .2       0  3868.2      .1       0  4976.9     .04       0
  5051.8      .1       0  6300.8      .2       0
#XS Ineff= 2 , 0
       0    4581    66.1    5121       0    66.1
Permanent Ineff=
       F       F
Bank Sta=4976.9,5051.8
XS Rating Curve= 0
Exp/Cntr=.3,.1

Type RM Length L Ch R = 1 ,9393.8  ,74.3,165.2,119.3
BEGIN DESCRIPTION:
Cross Section 9393.8-Interpolated
END DESCRIPTION:
XS GIS Cut Line= 6
      3143423.33     13905907.46      3143266.76     13905602.56
      3143019.54     13904663.13      3142838.05     13904246.27
       3142630.4     13903910.68      3142183.81     13903632.69
#Sta/Elev= 30
  3801.7   67.31  3901.7   66.06  4374.5   64.87  4404.5   65.68  4921.1   66.25
  4961.1   65.14 4982.31      63 4987.97   59.61 4998.62   56.08 5012.72   58.56
 5031.87    60.7 5039.68   63.31  5041.1   65.81  5081.1    65.5  5101.1   66.68
  5167.3   66.09  5197.3   67.15  5237.3   66.44  5337.3   67.19  5367.3   64.88
  5437.3   64.19  5457.3   65.19  5851.9   64.94  6046.6   66.69  6076.6   65.99
  6160.6   66.42  6216.6   65.97  6226.6   65.25  6426.6    66.3  6502.6   67.66
#Mann= 5 , 1 , 0
  3801.7      .2       0  3801.7      .1       0 4982.31     .04       0
 5039.68      .1       0  6160.6      .2       0
#XS Ineff= 2 , 0
       0    4902    67.2    5098       0    67.2
Permanent Ineff=
       F       F
Bank Sta=4982.31,5039.68
XS Rating Curve= 0
Exp/Cntr=.5,.3

Type RM Length L Ch R = 1 ,9228.6  ,60,60,60
BEGIN DESCRIPTION:
Upstream Section of Bridge/Culvert/Weir
END DESCRIPTION:
XS GIS Cut Line= 4
      3143437.41     13905885.79       3143146.5     13904787.71
       3142933.6     13904019.73      3142823.08     13903658.15
#Sta/Elev= 30
  3934.8   67.31  3938.5   66.81  3978.5   65.81  4401.2   66.01 4893.91   65.11
 4914.51   65.55 4939.87   65.54 4964.61   65.93 4981.75   62.43 4982.31   62.83
 4987.97   59.44 4993.18    57.2 4995.48    56.5 4998.62   55.91 5003.29   56.17
  5004.9   56.74 5005.44   56.68 5012.72   58.39 5025.05    59.5 5026.86   61.26
 5031.87   60.53 5039.68   63.14 5043.82   66.21 5075.76   66.33  5484.8   66.11
  5584.8   66.91  5674.8   66.41  5784.8   66.51  5873.3   65.41  6245.8   66.71
#Mann= 5 , 1 , 0
  3934.8      .2       0  3938.5      .1       0 4982.31     .04       0
 5039.68      .1       0  6245.8      .2       0
#XS Ineff= 2 , 0
       0    4971    67.2    5038       0    67.2
Permanent Ineff=
       F       F
Bank Sta=4982.31,5039.68
XS Rating Curve= 0
Exp/Cntr=.5,.3

Type RM Length L Ch R = 3 ,9198.6  ,,,
BEGIN DESCRIPTION:
SOUTHERN PACIFIC RAILROAD, SKEW ANGLE OF 40 DEGREES
Structure ID: P33-08
END DESCRIPTION:
Bridge Culvert--1,0,-1,-1, 0
Deck Dist Width WeirC Skew NumUp NumDn MinLoCord MaxHiCord MaxSubmerge Is_Ogee
10,40,2.6,0, 60, 60, , , .95, 0, 1,1,,
  3934.8  3938.5  3978.5  4401.2  4634.8  4671.2  4829.8 4893.91 4914.51  4921.5
 4939.87  4952.2 4964.61  4976.4 4981.75 4981.83 4981.92 4982.08 4982.31 4987.97
 4993.18 4994.48 4995.48 4998.62 5003.29  5004.9 5005.44 5012.72 5016.32 5025.05
 5026.86 5026.96 5027.62 5027.73 5031.87  5036.2 5039.68 5043.82  5073.2 5075.76
  5117.2  5127.8 5179.01  5188.8  5233.6  5241.2  5404.8  5454.8  5484.8  5534.8
  5584.8  5624.8  5674.8  5784.8  5833.3  5873.3  5890.8  6203.3  6239.8  6245.8
    67.3    67.3   67.29   67.23    67.2   67.25   67.48   67.41   67.39   67.38
   67.33   67.29   67.29   67.29   67.29   67.29   67.29   67.29   67.29   67.28
   67.28   67.28   67.28   67.28   67.27   67.27   67.27   67.27   67.26   67.26
   67.26   67.26   67.26   67.26   67.25   67.25   67.26   67.27   67.36   67.36
   67.42   67.43   67.44   67.44   67.37   67.37   67.33   67.31   67.31   67.29
   67.28   67.27   67.26   67.23   67.21    67.2    67.2   67.11    67.1    66.7
    67.3    66.8    65.8      66   65.57    65.5   65.22    65.1   65.54   65.54
   65.53   65.72   65.92   63.51   62.42   62.48   65.19   65.19   65.19   65.18
   65.18   65.18   65.18   65.18   65.17   65.17   65.17   65.17   65.16   65.16
   65.16   65.16   65.16   61.12   60.52   61.97   63.13    66.2   66.31   66.32
   66.33   66.32   66.27   66.27    66.3    66.3    66.1    66.2    66.1    66.6
    66.9    66.8    66.4    66.5    65.8    65.4   65.45    66.4   66.66    66.7
  3934.8  3938.5  3978.5  4401.2  4634.8  4671.2  4829.8 4893.91 4914.51  4921.5
 4939.87  4952.2 4964.61  4976.4 4981.75 4981.83 4981.92 4982.08 4982.31 4987.97
 4993.18 4994.48 4995.48 4998.62 5003.29  5004.9 5005.44 5012.72 5016.32 5025.05
 5026.86 5026.96 5027.62 5027.73 5031.87  5036.2 5039.68 5043.82  5073.2 5075.76
  5117.2  5127.8 5179.01  5188.8  5233.6  5241.2  5404.8  5454.8  5484.8  5534.8
  5584.8  5624.8  5674.8  5784.8  5833.3  5873.3  5890.8  6203.3  6239.8  6245.8
    67.3    67.3   67.29   67.23    67.2   67.25   67.48   67.41   67.39   67.38
   67.33   67.29   67.29   67.29   67.29   67.29   67.29   67.29   67.29   67.28
   67.28   67.28   67.28   67.28   67.27   67.27   67.27   67.27   67.26   67.26
   67.26   67.26   67.26   67.26   67.25   67.25   67.26   67.27   67.36   67.36
   67.42   67.43   67.44   67.44   67.37   67.37   67.33   67.31   67.31   67.29
   67.28   67.27   67.26   67.23   67.21    67.2    67.2   67.11    67.1    66.7
    67.2    66.7    65.7    65.9   65.47    65.4   65.12      65   65.44   65.44
   65.43   65.62   65.82   63.41   62.32   62.38   65.09   65.09   65.09   65.08
   65.08   65.08   65.08   65.08   65.07   65.07   65.07   65.07   65.06   65.06
   65.06   65.06   65.06   61.02   60.42   61.87   63.03    66.1   66.21   66.22
   66.23   66.22   66.17   66.17    66.2    66.2      66    66.1      66    66.5
    66.8    66.7    66.3    66.4    65.7    65.3   65.35    66.3   66.56    66.6
Pier Skew, UpSta & Num, DnSta & Num=  ,4993.2, 2 ,4993.2, 2 , 0 , 0 , 0 ,,
     1.2     1.2
      56   66.18
     1.2     1.2
    55.9   66.08
Pier Skew, UpSta & Num, DnSta & Num=  ,5004.9, 2 ,5004.9, 2 , 0 , 0 , 0 ,,
     1.2     1.2
   55.52   66.17
     1.2     1.2
   55.42   66.07
Pier Skew, UpSta & Num, DnSta & Num=  ,5016.3, 2 ,5016.3, 2 , 0 , 0 , 0 ,,
     1.2     1.2
   57.62   66.16
     1.2     1.2
   57.52   66.06
BR Coef= 1 , 1 , 0 ,1.25, 0 ,,,.8,0,2,0,
WSPro=,,,, 1 ,,,, 0 ,,,, 0 ,,,,-1 ,-1 ,-1 , 0 , 0 , 0 , 0 , 0
BR U #Sta/Elev= 60
  3934.8    67.3  3938.5    66.8  3978.5    65.8  4401.2      66  4634.8   65.57
  4671.2    65.5  4829.8   65.22 4893.91    65.1 4914.51   65.54  4921.5   65.54
 4939.87   65.53  4952.2   65.72 4964.61   65.92  4976.4   63.51 4981.75   62.42
 4981.83   62.48 4981.92   62.54 4982.08   62.66 4982.31   62.82 4987.97   59.43
 4993.18   57.19 4994.48   56.77 4995.48   56.49 4998.62    55.9 5003.29   56.16
  5004.9   56.73 5005.44   56.67 5012.72   58.38 5016.32   58.67 5025.05   59.49
 5026.86   61.25 5026.96   61.24 5027.62   61.14 5027.73   61.12 5031.87   60.52
  5036.2   61.97 5039.68   63.13 5043.82    66.2  5073.2   66.31 5075.76   66.32
  5117.2   66.33  5127.8   66.32 5179.01   66.27  5188.8   66.27  5233.6    66.3
  5241.2    66.3  5404.8    66.1  5454.8    66.2  5484.8    66.1  5534.8    66.6
  5584.8    66.9  5624.8    66.8  5674.8    66.4  5784.8    66.5  5833.3    65.8
  5873.3    65.4  5890.8   65.45  6203.3    66.4  6239.8   66.66  6245.8    66.7
BR U #Mann= 5
  3934.8      .2  3938.5      .1 4982.31     .04 5039.68      .1  6245.8      .2
BR U Banks=4982.31,5039.68
BR D #Sta/Elev= 60
  3934.8    67.2  3938.5    66.7  3978.5    65.7  4401.2    65.9  4634.8   65.47
  4671.2    65.4  4829.8   65.12 4893.91      65 4914.51   65.44  4921.5   65.44
 4939.87   65.43  4952.2   65.62 4964.61   65.82  4976.4   63.41 4981.75   62.32
 4981.83   62.38 4981.92   62.44 4982.08   62.56 4982.31   62.72 4987.97   59.33
 4993.18   57.09 4994.48   56.67 4995.48   56.39 4998.62    55.8 5003.29   56.06
  5004.9   56.63 5005.44   56.57 5012.72   58.28 5016.32   58.57 5025.05   59.39
 5026.86   61.15 5026.96   61.14 5027.62   61.04 5027.73   61.02 5031.87   60.42
  5036.2   61.87 5039.68   63.03 5043.82    66.1  5073.2   66.21 5075.76   66.22
  5117.2   66.23  5127.8   66.22 5179.01   66.17  5188.8   66.17  5233.6    66.2
  5241.2    66.2  5404.8      66  5454.8    66.1  5484.8      66  5534.8    66.5
  5584.8    66.8  5624.8    66.7  5674.8    66.3  5784.8    66.4  5833.3    65.7
  5873.3    65.3  5890.8   65.35  6203.3    66.3  6239.8   66.56  6245.8    66.6
BR D #Mann= 5
  3934.8      .2  3938.5      .1 4982.31     .04 5039.68      .1  6245.8      .2
BR D Banks=4982.31,5039.68
BC Design=,, 0 ,, 0 ,,,,,,

Type RM Length L Ch R = 1 ,9168.6  ,453.2,453.2,453.2
BEGIN DESCRIPTION:
Downstream Section of Bridge/Culvert/Weir
END DESCRIPTION:
XS GIS Cut Line= 4
      3143495.75     13905899.78      3143204.84     13904801.71
      3142991.94     13904033.73      3142881.42     13903672.14
#Sta/Elev= 30
  3934.8   67.16  3938.5   66.66  3978.5   65.66  4401.2   65.86 4893.91   64.96
 4914.51    65.4 4939.87   65.39 4964.61   65.78 4981.75   62.28 4982.31   62.68
 4987.97   59.29 4993.18   57.05 4995.48   56.35 4998.62   55.76 5003.29   56.02
  5004.9   56.59 5005.44   56.53 5012.72   58.24 5025.05   59.35 5026.86   61.11
 5031.87   60.38 5039.68   62.99 5043.82   66.06 5075.76   66.18  5484.8   65.96
  5584.8   66.76  5674.8   66.26  5784.8   66.36  5873.3   65.26  6245.8   66.56
#Mann= 5 , 1 , 0
  3934.8      .2       0  3938.5      .1       0 4982.31     .04       0
 5039.68      .1       0  6245.8      .2       0
#XS Ineff= 2 , 0
       0    4971      66    5038       0      66
Permanent Ineff=
       F       F
Bank Sta=4982.31,5039.68
XS Rating Curve= 0
Exp/Cntr=.5,.3

Type RM Length L Ch R = 1 ,8715.4  ,503.6,494.9,466.2
BEGIN DESCRIPTION:
Cross Section 8715.4-Interpolated
END DESCRIPTION:
XS GIS Cut Line= 6
      3143908.27     13906189.97      3143826.49     13905982.39
       3143688.1     13905303.02      3143662.94      13904787.2
       3143591.7      13903736.5      3143183.39     13903159.38
#Sta/Elev= 30
  3725.5   67.11  3776.5   67.04  3815.5   65.45  3855.5   64.96  3948.6   65.59
  4058.6   64.55  4508.6   64.58  4554.1   65.45  4652.3   65.53    4861   63.61
  4970.7   64.11  4976.9   60.92  4991.1   55.29  4998.2      54  5004.3   54.26
  5016.6   56.48  5041.6   58.62  5051.8   61.23  5055.7   66.04  5090.7   66.17
  5158.4   63.96  6033.4   64.85  6166.4   66.35  6274.4   65.17  6547.5   65.08
  6596.5   66.66  6638.5   65.54  6715.5   65.28  6897.5   65.42  6918.5   66.01
#Mann= 9 , 1 , 0
  3725.5      .2       0  3725.5      .1       0  3776.5     .14       0
  4554.1      .1       0  4652.3     .07       0    4861     .14       0
  4976.9     .04       0  5051.8     .14       0  6274.4      .2       0
#XS Ineff= 2 , 0
       0    4515      66    5485       0    66.2
Permanent Ineff=
       F       F
Bank Sta=4976.9,5051.8
XS Rating Curve= 0
Exp/Cntr=.3,.1