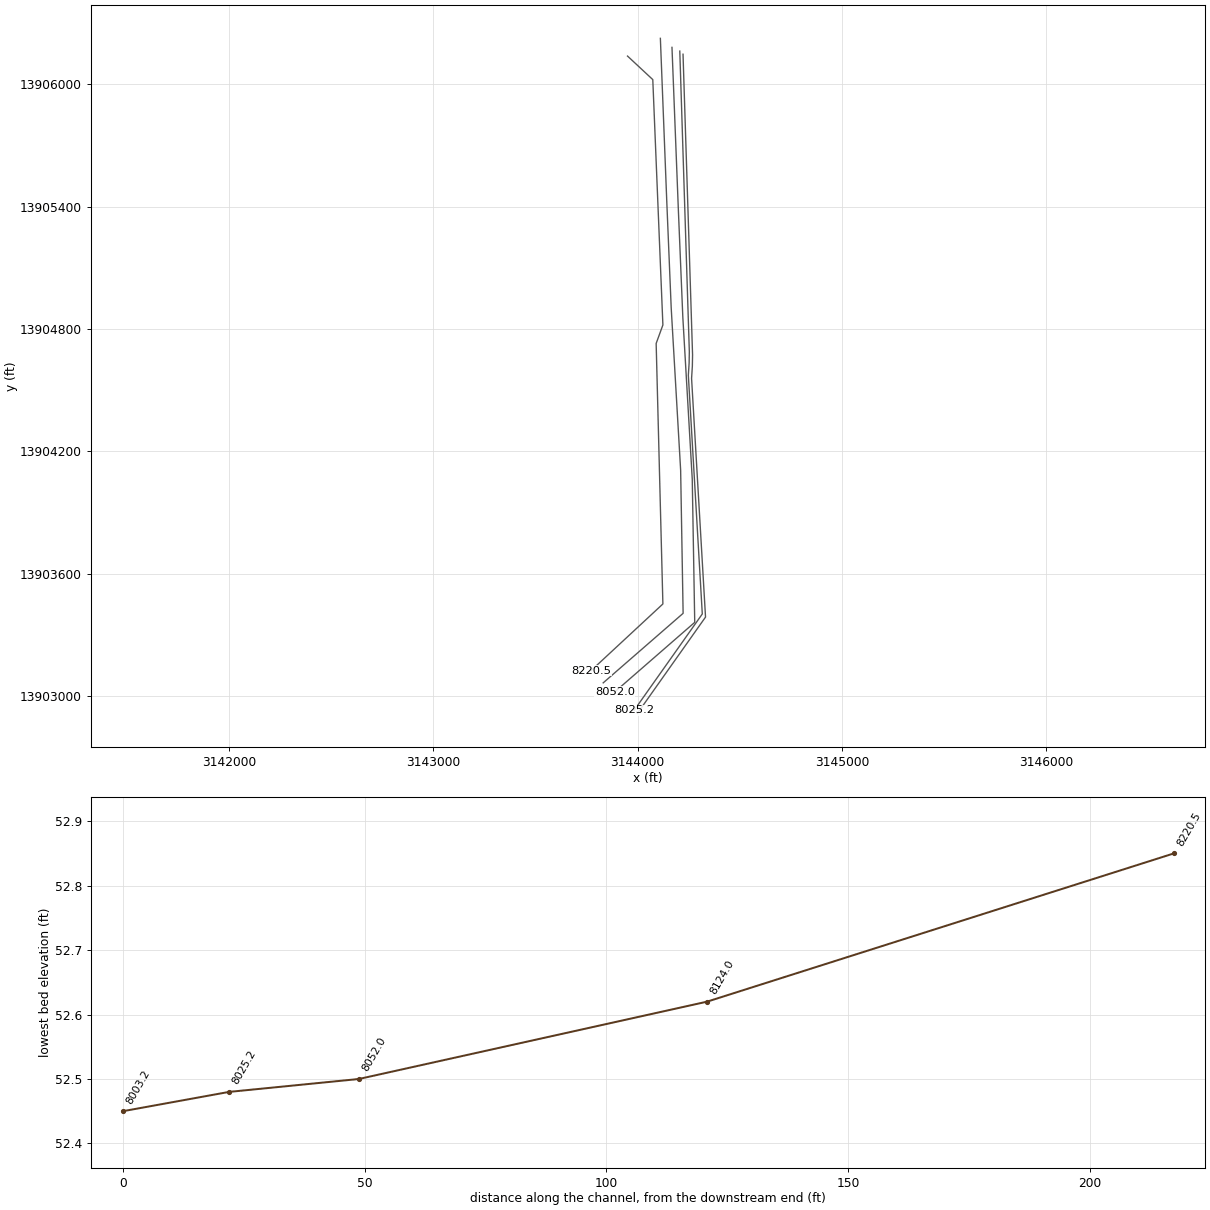
HEC-RAS study P133-00-00.PRJ: P133-00-00

--- P133-00-00.g01 (geometry) --- (continued)

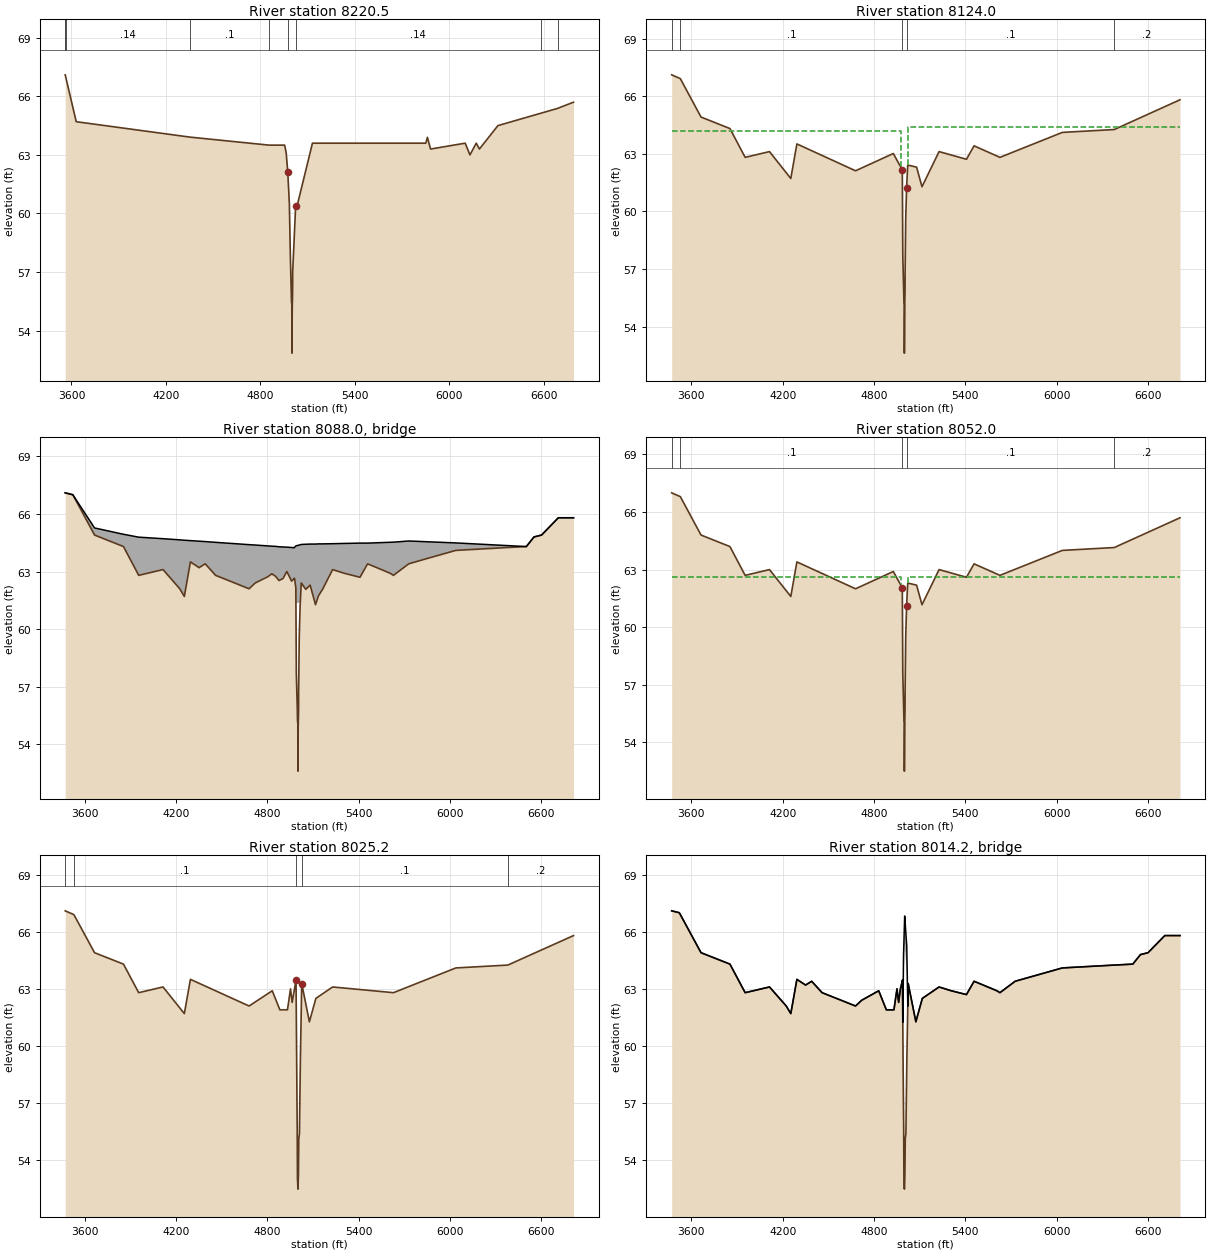
Type RM Length L Ch R = 1 ,8220.5  ,58.7,96.5,95.2
BEGIN DESCRIPTION:
Cross Section 8220.5-Interpolated
END DESCRIPTION:
XS GIS Cut Line= 6
      3143950.73      13906138.2      3144074.34     13906022.83
      3144123.78      13904819.7      3144090.82     13904729.06
      3144123.78     13903451.76      3143772.31     13903124.81
#Sta/Elev= 30
  3560.4    67.1  3564.2   66.97  3630.4    64.7  4352.7   63.91  4854.7    63.5
  4953.6    63.5  4963.6    63.1  4973.6    62.1  4983.6    60.5 4989.66   57.92
 4997.24   55.45 4999.16   55.37 4999.85   52.85 5001.84   55.15 5004.37   56.11
 5004.75   57.03  5023.6    60.4  5030.1    60.3  5130.1    63.6  5850.1    63.6
  5860.1    63.9  5880.1    63.3  6100.1    63.6  6130.1      63  6170.1    63.6
  6190.1    63.3  6307.8    64.5  6578.6   65.13  6686.3   65.38  6787.8    65.7
#Mann= 9 , 1 , 0
  3560.4      .2       0  3560.4      .1       0  3564.2     .14       0
  4352.7      .1       0  4854.7     .14       0  4973.6     .04       0
  5023.6     .14       0  6578.6      .1       0  6686.3      .2       0
Bank Sta=4973.6,5023.6
XS Rating Curve= 0
Exp/Cntr=.5,.3

Type RM Length L Ch R = 1 ,8124.0  ,72,72,72
BEGIN DESCRIPTION:
Upstream Section of Bridge/Culvert/Weir
END DESCRIPTION:
XS GIS Cut Line= 6
      3144111.45     13906225.16      3144142.83     13905424.02
      3144164.47      13904902.7      3144210.62     13904108.01
      3144222.76     13903405.86      3143831.72     13903064.94
#Sta/Elev= 30
  3470.6   67.12  3527.7   66.92  3663.5   64.92  3853.5   64.32  3953.5   62.82
  4113.5   63.12  4253.5   61.72  4293.5   63.52    4679   62.12 4927.08   63.02
 4986.21   62.17 4989.56   57.69 4997.24   55.22 4999.16   55.14 4999.85   52.62
 5001.84   54.92 5004.37   55.88 5004.65    56.8 5008.66    59.6 5014.25   61.21
 5021.98   62.42  5080.2   62.31 5115.67   61.29  5227.9   63.12  5407.9   62.72
  5457.9   63.42  5627.9   62.82  6037.9   64.12  6379.4   64.27  6811.2   65.82
#Mann= 5 , 1 , 0
  3470.6      .2       0  3527.7      .1       0 4986.21     .04       0
 5014.25      .1       0  6379.4      .2       0
#XS Ineff= 2 , 0
       0    4978    64.2    5025       0    64.4
Permanent Ineff=
       F       F
Bank Sta=4986.21,5014.25
XS Rating Curve= 0
Exp/Cntr=.5,.3

Type RM Length L Ch R = 3 ,8088.0  ,,,
BEGIN DESCRIPTION:
SMITH ROAD, SKEW ANGLE OF 40 DEGREES
Structure ID: P33-7
END DESCRIPTION:
Bridge Culvert--1,0,-1,-1, 0
Deck Dist Width WeirC Skew NumUp NumDn MinLoCord MaxHiCord MaxSubmerge Is_Ogee
10,52,2.6,0, 44, 44, , , .95, 0, 1,1,,
  3470.6  3520.6  3663.5  3853.5  3953.5  4113.5  4223.5  4253.5  4293.5  4350.6
  4390.6    4459    4679    4719 4828.49 4852.93  4875.3 4901.42 4927.08 4958.33
 4975.39 4977.48 4986.21 4987.88 4987.97  5014.6 5014.71 5021.98 5051.55  5080.2
 5115.67 5134.89 5163.23  5227.9  5407.9  5457.9  5627.9  5727.9  6037.9  6501.2
  6551.2  6601.2  6711.2  6811.2
    67.1      67   65.27   64.94   64.79   64.71   64.65   64.63   64.61   64.58
   64.56   64.52    64.4   64.38   64.32   64.31   64.29   64.28   64.27   64.25
   64.24   64.26   64.33   64.34   64.34   64.39   64.39   64.41   64.42   64.43
   64.43   64.44   64.44   64.45   64.48   64.48   64.53   64.59   64.49    64.3
    64.8    64.9    65.8    65.8
    67.1      67    64.9    64.3    62.8    63.1    62.1    61.7    63.5    63.2
    63.4    62.8    62.1    62.4   62.88   62.75   62.53   62.63      63    62.5
   62.63   62.65   62.15   59.92   61.34   61.39   61.26    62.4   62.07   62.29
   61.27   61.73   62.09    63.1    62.7    63.4    62.8    63.4    64.1    64.3
    64.8    64.9    65.8    65.8
  3470.6  3520.6  3663.5  3853.5  3953.5  4113.5  4223.5  4253.5  4293.5  4350.6
  4390.6    4459    4679    4719 4828.49 4852.93  4875.3 4901.42 4927.08 4958.33
 4975.39 4977.48 4986.21 4987.88 4987.97  5014.6 5014.71 5021.98 5051.55  5080.2
 5115.67 5134.89 5163.23  5227.9  5407.9  5457.9  5627.9  5727.9  6037.9  6501.2
  6551.2  6601.2  6711.2  6811.2
    67.1      67   65.27   64.94   64.79   64.71   64.65   64.63   64.61   64.58
   64.56   64.52    64.4   64.38   64.32   64.31   64.29   64.28   64.27   64.25
   64.24   64.26   64.33   64.34   64.34   64.39   64.39   64.41   64.42   64.43
   64.43   64.44   64.44   64.45   64.48   64.48   64.53   64.59   64.49    64.3
    64.8    64.9    65.8    65.8
      67    66.9    64.8    64.2    62.7      63      62    61.6    63.4    63.1
    63.3    62.7      62    62.3   62.78   62.65   62.43   62.53    62.9    62.4
   62.53   62.55   62.05   59.82   61.24   61.29   61.16    62.3   61.97   62.19
   61.17   61.63   61.99      63    62.6    63.3    62.7    63.3      64    64.2
    64.7    64.8    65.7    65.7
Abutment Skew #Up #Dn= , 2 , 2
 4987.77 4989.66
   61.34   57.64
 4987.77 4989.66
   61.24   57.54
Abutment Skew #Up #Dn= , 2 , 2
 5004.75  5014.8
   56.85   61.39
 5004.75  5014.8
   56.75   61.29
BR Coef= 1 , 1 , 0 ,1.25, 0 ,,,.8,0,2,0,
WSPro=,,,, 1 ,,,, 0 ,,,, 0 ,,,,-1 ,-1 ,-1 , 0 , 0 , 0 , 0 , 0
BR U #Sta/Elev= 71
  3470.6    67.1  3520.6      67  3527.7    66.9  3663.5    64.9  3853.5    64.3
  3937.7   63.04  3953.5    62.8  4113.5    63.1  4223.5    62.1  4253.5    61.7
  4293.5    63.5  4350.6    63.2  4390.6    63.4    4459    62.8    4679    62.1
    4719    62.4 4802.68   62.73 4828.49   62.88 4852.93   62.75  4875.3   62.53
 4901.42   62.63 4927.08      63 4958.33    62.5 4975.39   62.63  4975.5   62.63
 4975.61   62.64 4977.48   62.65  4984.3   62.26 4986.21   62.15 4987.88   59.92
 4987.97    59.8 4989.56   57.67 4989.66   57.64 4995.63   55.91 4997.24    55.2
 4999.16   55.12 4999.85    52.6 5001.84    54.9 5004.37   55.86 5004.65   56.78
 5004.75   56.85 5008.66   59.58 5014.25   61.19  5014.6   61.24 5014.71   61.26
 5021.98    62.4 5027.39   62.34  5027.5   62.34 5027.61   62.34 5051.55   62.07
  5080.2   62.29 5115.67   61.27 5134.89   61.73 5163.23   62.09  5227.9    63.1
  5307.9    62.9  5407.9    62.7  5457.9    63.4  5564.1   63.05  5607.9    62.9
  5627.9    62.8  5727.9    63.4  5750.1   63.45  5850.1   63.68  6037.9    64.1
  6379.4   64.25  6501.2    64.3  6551.2    64.8  6601.2    64.9  6711.2    65.8
  6811.2    65.8
BR U #Mann= 5
  3470.6      .2  3527.7      .1 4986.21     .04 5014.25      .1  6379.4      .2
BR U Banks=4986.21,5014.25
BR D #Sta/Elev= 71
  3470.6      67  3520.6    66.9  3527.7    66.8  3663.5    64.8  3853.5    64.2
  3937.7   62.94  3953.5    62.7  4113.5      63  4223.5      62  4253.5    61.6
  4293.5    63.4  4350.6    63.1  4390.6    63.3    4459    62.7    4679      62
    4719    62.3 4802.68   62.63 4828.49   62.78 4852.93   62.65  4875.3   62.43
 4901.42   62.53 4927.08    62.9 4958.33    62.4 4975.39   62.53  4975.5   62.53
 4975.61   62.54 4977.48   62.55  4984.3   62.16 4986.21   62.05 4987.88   59.82
 4987.97    59.7 4989.56   57.57 4989.66   57.54 4995.63   55.81 4997.24    55.1
 4999.16   55.02 4999.85    52.5 5001.84    54.8 5004.37   55.76 5004.65   56.68
 5004.75   56.75 5008.66   59.48 5014.25   61.09  5014.6   61.14 5014.71   61.16
 5021.98    62.3 5027.39   62.24  5027.5   62.24 5027.61   62.24 5051.55   61.97
  5080.2   62.19 5115.67   61.17 5134.89   61.63 5163.23   61.99  5227.9      63
  5307.9    62.8  5407.9    62.6  5457.9    63.3  5564.1   62.95  5607.9    62.8
  5627.9    62.7  5727.9    63.3  5750.1   63.35  5850.1   63.58  6037.9      64
  6379.4   64.15  6501.2    64.2  6551.2    64.7  6601.2    64.8  6711.2    65.7
  6811.2    65.7
BR D #Mann= 5
  3470.6      .2  3527.7      .1 4986.21     .04 5014.25      .1  6379.4      .2
BR D Banks=4986.21,5014.25
BC Design=,, 0 ,, 0 ,,,,,,

Type RM Length L Ch R = 1 ,8052.0  ,26.8,26.8,26.8
BEGIN DESCRIPTION:
Downstream Section of Bridge/Culvert/Weir
END DESCRIPTION:
XS GIS Cut Line= 6
      3144168.24     13906180.91      3144199.63     13905379.76
      3144221.27     13904858.44      3144267.42     13904063.75
      3144279.56      13903361.6      3143888.52     13903020.68
#Sta/Elev= 30
  3470.6      67  3527.7    66.8  3663.5    64.8  3853.5    64.2  3953.5    62.7
  4113.5      63  4253.5    61.6  4293.5    63.4    4679      62 4927.08    62.9
 4986.21   62.05 4989.56   57.57 4997.24    55.1 4999.16   55.02 4999.85    52.5
 5001.84    54.8 5004.37   55.76 5004.65   56.68 5008.66   59.48 5014.25   61.09
 5021.98    62.3  5080.2   62.19 5115.67   61.17  5227.9      63  5407.9    62.6
  5457.9    63.3  5627.9    62.7  6037.9      64  6379.4   64.15  6811.2    65.7
#Mann= 5 , 1 , 0
  3470.6      .2       0  3527.7      .1       0 4986.21     .04       0
 5014.25      .1       0  6379.4      .2       0
#XS Ineff= 2 , 0
       0    4978    62.6    5025       0    62.6
Permanent Ineff=
       F       F
Bank Sta=4986.21,5014.25
XS Rating Curve= 0
Exp/Cntr=.5,.3

Type RM Length L Ch R = 1 ,8025.2  ,22,22,22
BEGIN DESCRIPTION:
Upstream Section of Bridge/Culvert/Weir
END DESCRIPTION:
XS GIS Cut Line= 6
      3144206.47     13906162.54      3144253.14     13904688.66
      3144252.13     13904633.11      3144248.32     13904573.02
      3144316.56     13903402.68      3143983.31     13902930.56
#Sta/Elev= 30
  3470.6    67.1  3527.7    66.9  3663.5    64.9  3853.5    64.3  3953.5    62.8
  4113.5    63.1  4253.5    61.7  4293.5    63.5    4679    62.1  4831.3    62.9
  4881.3    61.9  4931.3    61.9  4951.3      63 4962.19   62.29 4987.54   63.46
 4995.36   55.54 4996.89   53.02 5000.26   52.48 5003.09   53.18 5005.78   55.13
 5009.84   55.39 5016.35   59.37 5024.85   63.28 5075.41   61.27  5117.9    62.5
  5227.9    63.1  5627.9    62.8  6037.9    64.1  6379.4   64.25  6811.2    65.8
#Mann= 5 , 1 , 0
  3470.6      .2       0  3527.7      .1       0 4987.54     .04       0
 5024.85      .1       0  6379.4      .2       0
#XS Ineff= 2 , 0
       0    4977    61.3    5035       0    61.6
Permanent Ineff=
       F       F
Bank Sta=4987.54,5024.85
XS Rating Curve= 0
Exp/Cntr=.5,.3

Type RM Length L Ch R = 3 ,8014.2  ,,,
BEGIN DESCRIPTION:
18" ARCHED PIPELINE, SKEW ANGLE OF 40 DEGREES
END DESCRIPTION:
Bridge Culvert--1,0,-1,-1, 0
Deck Dist Width WeirC Skew NumUp NumDn MinLoCord MaxHiCord MaxSubmerge Is_Ogee
10,2,2.6,0, 59, 59, , , .95, 0, 1,1,,
  3470.6  3520.6  3527.7  3663.5  3853.5  3953.5  4113.5  4223.5  4253.5  4293.5
  4350.6  4390.6    4459    4679    4719  4831.3  4881.3  4931.3  4951.3 4962.19
 4973.83 4987.35 4987.44 4987.54 4989.54 4991.68 4994.36 4995.36 4996.89 4999.34
 5000.26 5001.79 5002.02 5003.09 5005.78 5009.84  5015.5 5016.35 5021.02 5022.24
 5024.85 5027.03 5027.14 5075.41  5117.9  5227.9  5307.9  5407.9  5457.9  5607.9
  5627.9  5727.9  6037.9  6379.4  6501.2  6551.2  6601.2  6711.2  6811.2
    67.1      67    66.9    64.9    64.3    62.8    63.1    62.1    61.7    63.5
    63.2    63.4    62.8    62.1    62.4    62.9    61.9    61.9      63   62.29
      63   63.45   63.46   63.46   61.24   62.65   64.79   65.06   65.48   66.16
   66.41   66.83    66.8   66.68   66.38   65.91   65.27   64.87    62.7   62.09
   63.28   63.19   63.19   61.27    62.5    63.1    62.9    62.7    63.4    62.9
    62.8    63.4    64.1   64.25    64.3    64.8    64.9    65.8    65.8
    67.1      67    66.9    64.9    64.3    62.8    63.1    62.1    61.7    63.5
    63.2    63.4    62.8    62.1    62.4    62.9    61.9    61.9      63   62.29
      63   63.45   63.46   63.46   61.23   61.15   63.29   63.56   63.98   64.66
   64.91   65.33    65.3   65.18   64.88   64.41   63.77   63.37   61.52   62.08
   63.28   63.19   63.19   61.27    62.5    63.1    62.9    62.7    63.4    62.9
    62.8    63.4    64.1   64.25    64.3    64.8    64.9    65.8    65.8
  3470.6  3520.6  3527.7  3663.5  3853.5  3953.5  4113.5  4223.5  4253.5  4293.5
  4350.6  4390.6    4459    4679    4719  4831.3  4881.3  4931.3  4951.3 4962.19
 4973.83 4987.35 4987.44 4987.54 4989.54 4991.68 4994.36 4995.36 4996.89 4999.34
 5000.26 5001.79 5002.02 5003.09 5005.78 5009.84  5015.5 5016.35 5021.02 5022.24
 5024.85 5027.03 5027.14 5075.41  5117.9  5227.9  5307.9  5407.9  5457.9  5607.9
  5627.9  5727.9  6037.9  6379.4  6501.2  6551.2  6601.2  6711.2  6811.2
    67.1      67    66.9    64.9    64.3    62.8    63.1    62.1    61.7    63.5
    63.2    63.4    62.8    62.1    62.4    62.9    61.9    61.9      63   62.29
      63   63.45   63.46   63.46   61.24   62.65   64.79   65.06   65.48   66.16
   66.41   66.83    66.8   66.68   66.38   65.91   65.27   64.87    62.7   62.09
   63.28   63.19   63.19   61.27    62.5    63.1    62.9    62.7    63.4    62.9
    62.8    63.4    64.1   64.25    64.3    64.8    64.9    65.8    65.8
    67.1      67    66.9    64.9    64.3    62.8    63.1    62.1    61.7    63.5
    63.2    63.4    62.8    62.1    62.4    62.9    61.9    61.9      63   62.29
      63   63.45   63.46   63.46   61.23   61.15   63.29   63.56   63.98   64.66
   64.91   65.33    65.3   65.18   64.88   64.41   63.77   63.37   61.52   62.08
   63.28   63.19   63.19   61.27    62.5    63.1    62.9    62.7    63.4    62.9
    62.8    63.4    64.1   64.25    64.3    64.8    64.9    65.8    65.8
BR Coef= 1 , 1 , 0 ,1.25, 0 ,,,.8,0,2,0,
WSPro=,,,, 1 ,,,, 0 ,,,, 0 ,,,,-1 ,-1 ,-1 , 0 , 0 , 0 , 0 , 0
BR U #Sta/Elev= 59
  3470.6    67.1  3520.6      67  3527.7    66.9  3663.5    64.9  3853.5    64.3
  3953.5    62.8  4113.5    63.1  4223.5    62.1  4253.5    61.7  4293.5    63.5
  4350.6    63.2  4390.6    63.4    4459    62.8    4679    62.1    4719    62.4
  4831.3    62.9  4881.3    61.9  4931.3    61.9  4951.3      63 4962.19   62.29
 4973.83      63 4987.35   63.45 4987.44   63.46 4987.54   63.46 4989.54   61.23
 4991.68   58.85 4994.36   56.44 4995.36   55.54 4996.89   53.02 4999.34   52.51
 5000.26   52.48 5001.79   52.78 5002.02   52.83 5003.09   53.18 5005.78   55.13
 5009.84   55.39  5015.5   58.85 5016.35   59.37 5021.02   61.52 5022.24   62.08
 5024.85   63.28 5027.03   63.19 5027.14   63.19 5075.41   61.27  5117.9    62.5
  5227.9    63.1  5307.9    62.9  5407.9    62.7  5457.9    63.4  5607.9    62.9
  5627.9    62.8  5727.9    63.4  6037.9    64.1  6379.4   64.25  6501.2    64.3
  6551.2    64.8  6601.2    64.9  6711.2    65.8  6811.2    65.8
BR U #Mann= 5
  3470.6      .2  3527.7      .1 4987.54     .04 5024.85      .1  6379.4      .2
BR U Banks=4987.54,5024.85
BR D #Sta/Elev= 59
  3470.6    67.1  3520.6      67  3527.7    66.9  3663.5    64.9  3853.5    64.3
  3953.5    62.8  4113.5    63.1  4223.5    62.1  4253.5    61.7  4293.5    63.5
  4350.6    63.2  4390.6    63.4    4459    62.8    4679    62.1    4719    62.4
  4831.3    62.9  4881.3    61.9  4931.3    61.9  4951.3      63 4962.19   62.29
 4973.83      63 4987.35   63.45 4987.44   63.46 4987.54   63.46 4989.54   61.23
 4991.68   58.85 4994.36   56.44 4995.36   55.54 4996.89   53.02 4999.34   52.51
 5000.26   52.48 5001.79   52.78 5002.02   52.83 5003.09   53.18 5005.78   55.13
 5009.84   55.39  5015.5   58.85 5016.35   59.37 5021.02   61.52 5022.24   62.08
 5024.85   63.28 5027.03   63.19 5027.14   63.19 5075.41   61.27  5117.9    62.5
  5227.9    63.1  5307.9    62.9  5407.9    62.7  5457.9    63.4  5607.9    62.9
  5627.9    62.8  5727.9    63.4  6037.9    64.1  6379.4   64.25  6501.2    64.3
  6551.2    64.8  6601.2    64.9  6711.2    65.8  6811.2    65.8
BR D #Mann= 5
  3470.6      .2  3527.7      .1 4987.54     .04 5024.85      .1  6379.4      .2
BR D Banks=4987.54,5024.85
BC Design=,, 0 ,, 0 ,,,,,,

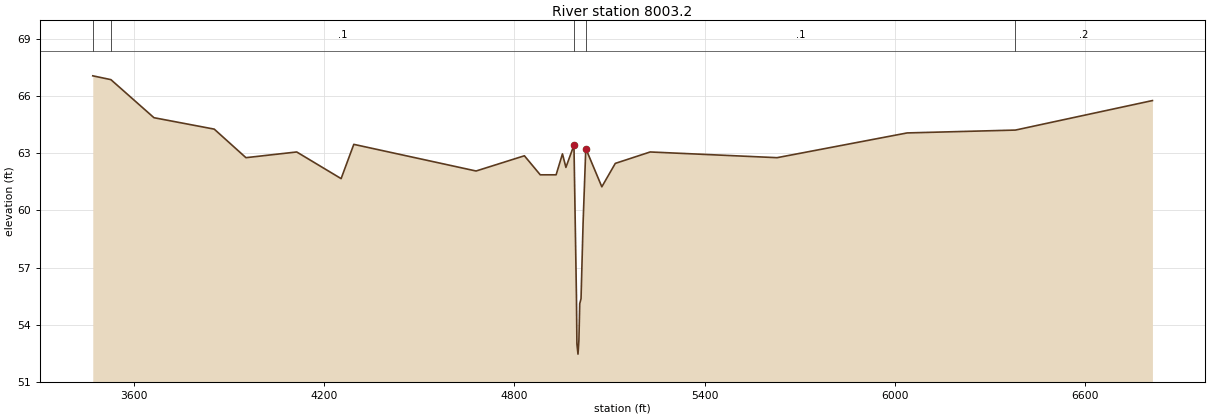
Type RM Length L Ch R = 1 ,8003.2  ,420.8,420.8,420.8
BEGIN DESCRIPTION:
Downstream Section of Bridge/Culvert/Weir
END DESCRIPTION:
XS GIS Cut Line= 6
       3144222.3     13906147.26      3144268.96     13904673.38
      3144267.95     13904617.83      3144264.14     13904557.74
      3144332.38      13903387.4      3143999.13     13902915.28
#Sta/Elev= 30
  3470.6   67.07  3527.7   66.87  3663.5   64.87  3853.5   64.27  3953.5   62.77
  4113.5   63.07  4253.5   61.67  4293.5   63.47    4679   62.07  4831.3   62.87
  4881.3   61.87  4931.3   61.87  4951.3   62.97 4962.19   62.26 4987.54   63.43
 4995.36   55.51 4996.89   52.99 5000.26   52.45 5003.09   53.15 5005.78    55.1
 5009.84   55.36 5016.35   59.34 5024.85   63.25 5075.41   61.24  5117.9   62.47
  5227.9   63.07  5627.9   62.77  6037.9   64.07  6379.4   64.22  6811.2   65.77
#Mann= 5 , 1 , 0
  3470.6      .2       0  3527.7      .1       0 4987.54     .04       0
 5024.85      .1       0  6379.4      .2       0
#XS Ineff= 2 , 0
       0    4977    61.3    5035       0    61.6
Permanent Ineff=
       F       F
Bank Sta=4987.54,5024.85
XS Rating Curve= 0
Exp/Cntr=.5,.3