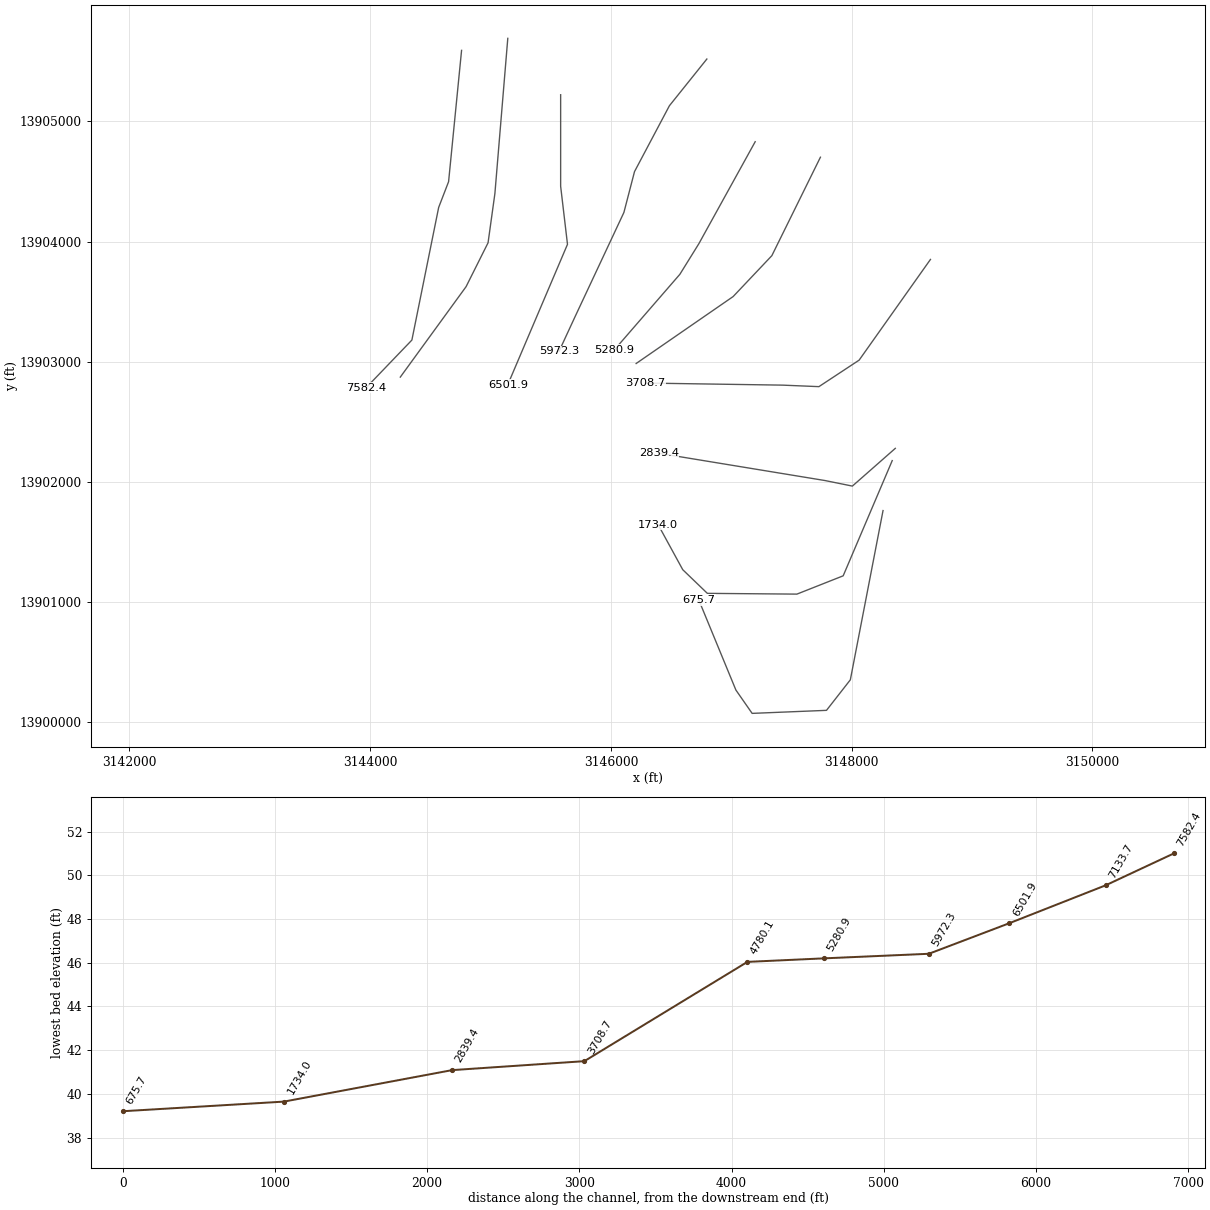
HEC-RAS study P133-00-00.PRJ: P133-00-00

--- P133-00-00.g01 (geometry) --- (continued)

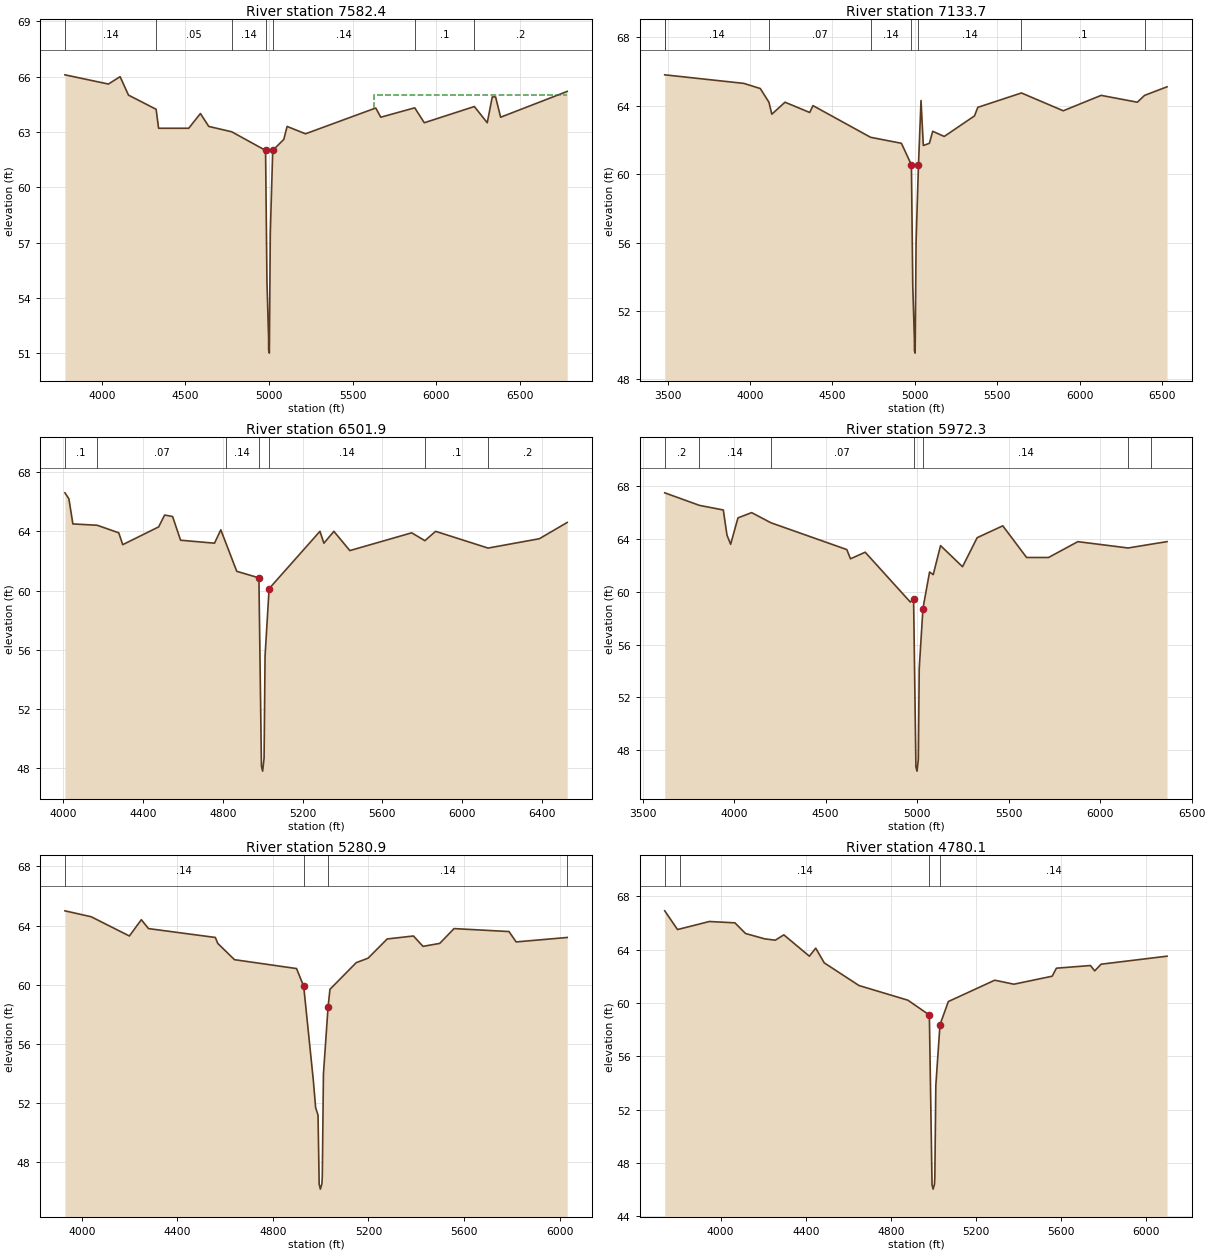
Type RM Length L Ch R = 1 ,7582.4  ,440.5,448.7,464.6
BEGIN DESCRIPTION:
Cross Section 7582.4-Interpolated
END DESCRIPTION:
XS GIS Cut Line= 5
      3144759.08     13905591.69      3144651.18     13904498.32
      3144568.78     13904284.06      3144346.28     13903179.82
      3143967.21     13902784.28
#Sta/Elev= 30
  3779.9    66.1  4039.9    65.6  4109.9      66  4159.9      65  4325.2   64.23
  4339.9    63.2  4519.9    63.2  4589.9      64  4639.9    63.3  4777.1   63.01
  4979.4      62  4987.6   54.91  4997.5   51.81  4997.6   51.15    5002      51
  5007.7   57.52  5022.2      62  5088.6    62.6  5108.1    63.3  5218.1    62.9
  5638.1    64.3  5668.1    63.8  5871.1   64.31  5928.1    63.5  6227.4   64.38
  6304.5    63.5  6334.5    64.9  6354.5    64.9  6384.5    63.8  6782.4    65.2
#Mann= 7 , 1 , 0
  3779.9     .14       0  4325.2     .05       0  4777.1     .14       0
  4979.4     .04       0  5022.2     .14       0  5871.1      .1       0
  6227.4      .2       0
#XS Ineff= 2 , 0
       0                    5630       0      65
Permanent Ineff=
       F       F
Bank Sta=4979.4,5022.2
XS Rating Curve= 0
Exp/Cntr=.3,.1

Type RM Length L Ch R = 1 ,7133.7  ,593.9,631.8,643.1
BEGIN DESCRIPTION:
Cross Section 7133.7
END DESCRIPTION:
XS GIS Cut Line= 5
      3145143.03     13905691.75      3145035.87     13904399.48
      3144979.13     13903989.74      3144796.33     13903624.12
      3144250.06     13902871.46
#Sta/Elev= 30
  3481.9    65.8  3961.9    65.3  4061.9      65  4114.5    64.2  4131.9    63.5
  4211.9    64.2  4361.9    63.6  4381.9      64  4731.6   62.15  4918.6    61.8
  4979.4   60.54  4987.6   53.45  4997.5   50.35  4997.6   49.69    5002   49.54
  5007.7   56.06  5022.2   60.54  5037.6    64.3  5051.6   61.67  5088.6    61.8
  5108.6    62.5  5178.6    62.2  5362.3    63.4  5382.3    63.9  5647.3   64.74
    5901    63.7    6131    64.6    6351    64.2  6394.8    64.6    6531    65.1
#Mann= 8 , 1 , 0
  3481.9      .2       0  3481.9     .14       0  4114.5     .07       0
  4731.6     .14       0  4979.4     .04       0  5022.2     .14       0
  5647.3      .1       0  6394.8      .2       0
Bank Sta=4979.4,5022.2
XS Rating Curve= 0
Exp/Cntr=.3,.1

Type RM Length L Ch R = 1 ,6501.9  ,655.4,529.6,518.1
BEGIN DESCRIPTION:
Cross Section 6501.9-Interpolated
END DESCRIPTION:
XS GIS Cut Line= 4
      3145582.04     13905222.08      3145582.04     13904460.49
      3145638.94     13903976.83      3145142.73     13902808.02
#Sta/Elev= 30
  4008.2    66.6  4028.2    66.2  4048.2    64.5  4170.3   64.41  4278.2    63.9
  4298.2    63.1  4478.2    64.3  4508.2    65.1  4548.2      65  4588.2    63.4
  4758.2    63.2  4789.8    64.1  4814.5   63.24  4869.8    61.3  4980.9   60.86
  4993.6   48.14  4999.6   47.81  5006.8   48.69  5011.7   55.58    5032   60.13
  5286.8      64  5306.8    63.2  5356.8      64  5436.8    62.7  5746.8    63.9
  5813.1   63.37  5866.8      64  6129.8   62.87  6386.8    63.5  6526.5    64.6
#Mann= 7 , 1 , 0
  4008.2      .1       0  4170.3     .07       0  4814.5     .14       0
  4980.9     .04       0    5032     .14       0  5813.1      .1       0
  6129.8      .2       0
Bank Sta=4980.9,5032
XS Rating Curve= 0
Exp/Cntr=.3,.1

Type RM Length L Ch R = 1 ,5972.3  ,711.1,691.4,684.7
BEGIN DESCRIPTION:
Cross Section 5972.3
END DESCRIPTION:
XS GIS Cut Line= 6
      3146796.67     13905519.39      3146485.73     13905130.72
      3146195.76     13904582.29      3146107.51     13904241.89
      3145697.76     13903365.66      3145569.13     13903086.98
#Sta/Elev= 30
  3621.4    67.5  3810.9   66.55  3941.4    66.2  3961.4    64.3  3981.4    63.6
  4021.4    65.6  4096.1      66  4201.7   65.23  4616.1    63.2  4636.1    62.5
  4716.5      63  4963.2   59.22  4980.9   59.46  4993.6   46.74  4999.6   46.41
  5006.8   47.29  5011.7   54.18    5032   58.73  5068.2    61.5  5088.2    61.3
  5128.2    63.5  5248.2    61.9  5328.2    64.1  5468.2      65  5598.2    62.6
  5718.2    62.6  5878.2    63.8  6152.6   63.32  6275.3    63.6  6365.4    63.8
#Mann= 7 , 1 , 0
  3621.4      .2       0  3810.9     .14       0  4201.7     .07       0
  4980.9     .04       0    5032     .14       0  6152.6      .1       0
  6275.3      .2       0
Bank Sta=4980.9,5032
XS Rating Curve= 0
Exp/Cntr=.3,.1

Type RM Length L Ch R = 1 ,5280.9  ,511.1,500.8,497.3
BEGIN DESCRIPTION:
Cross Section 5280.9-Interpolated
END DESCRIPTION:
XS GIS Cut Line= 4
      3147198.33     13904831.13      3146730.09     13903981.76
      3146572.48     13903727.16      3146026.91     13903096.71
#Sta/Elev= 30
  3929.2      65  4039.2    64.6  4199.2    63.3  4249.2    64.4  4279.2    63.8
  4559.2    63.2  4569.2    62.8  4639.2    61.7    4899    61.1    4929    59.9
    4969    53.6    4979    51.7    4989    51.2  4993.8   46.53  4998.9    46.2
  5005.3   46.57  5006.9   47.08  5011.6   53.97  5031.1   58.52    5039    59.7
    5149    61.5  5198.5    61.8  5278.5    63.1  5388.5    63.3  5428.5    62.6
  5498.5    62.8  5558.5    63.8  5788.5    63.6  5818.5    62.9  6032.2    63.2
#Mann= 4 , 1 , 0
  3929.2     .14       0    4929     .04       0  5031.1     .14       0
  6032.2      .2       0
Bank Sta=4929,5031.1
XS Rating Curve= 0
Exp/Cntr=.3,.1

Type RM Length L Ch R = 1 ,4780.1  ,1072.1,1071.4,1060.6
BEGIN DESCRIPTION:
Cross Section 4780.1
END DESCRIPTION:
XS GIS Cut Line= 4
      3147740.18     13904702.06      3147336.74     13903882.57
      3147015.25     13903542.17      3146209.34      13902984.7
#Sta/Elev= 30
    3737    66.9    3797    65.5  3810.5   65.55    3947    66.1    4067      66
    4117    65.2    4207    64.8    4257    64.7    4297    65.1    4417    63.5
    4447    64.1    4487      63  4650.4    61.3  4880.4    60.2  4981.2   59.09
  4993.8   46.37  4998.9   46.04  5005.3   46.41  5006.9   46.92  5011.6   53.81
  5031.1   58.36  5070.4    60.1  5288.6    61.7  5378.6    61.4  5558.6      62
  5578.6    62.6  5738.6    62.8  5758.6    62.4  5788.6    62.9  6098.6    63.5
#Mann= 4 , 1 , 0
    3737      .2       0  3810.5     .14       0  4981.2     .04       0
  5031.1     .14       0
Bank Sta=4981.2,5031.1
XS Rating Curve= 0
Exp/Cntr=.3,.1

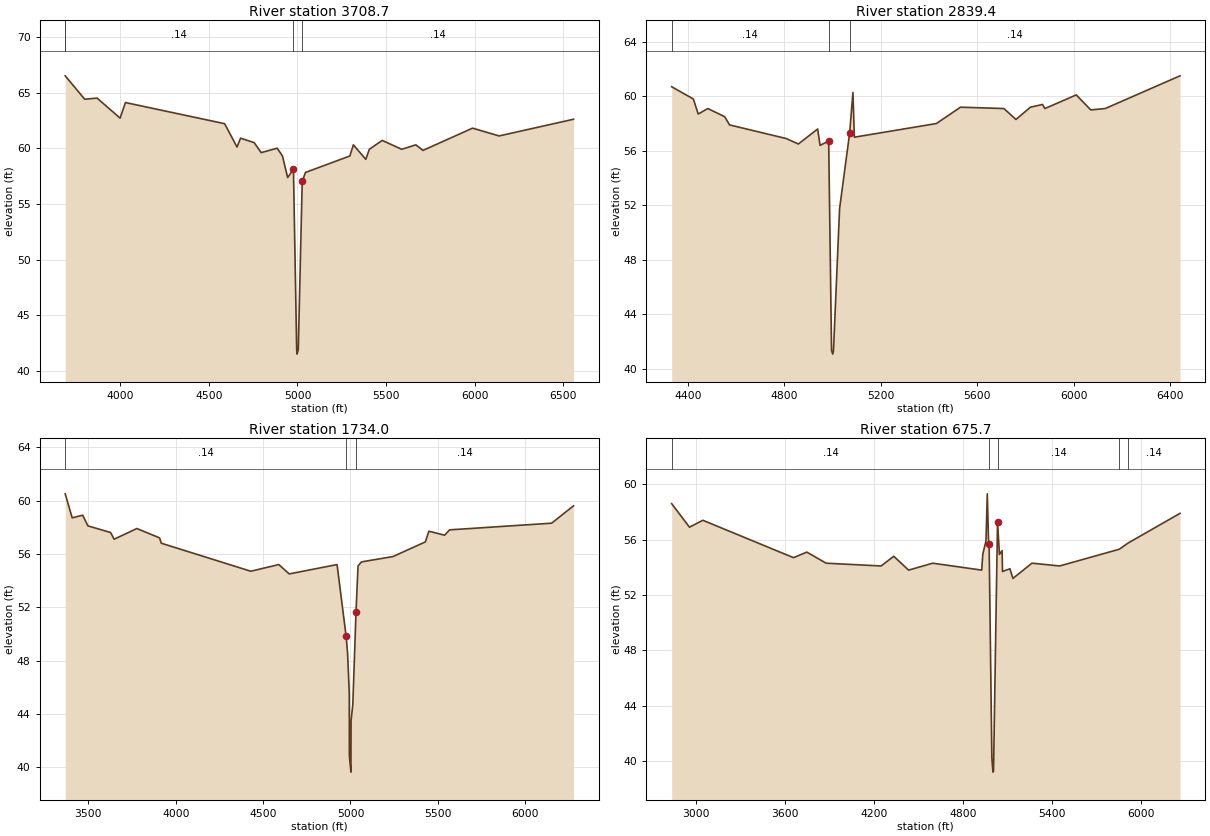
Type RM Length L Ch R = 1 ,3708.7  ,892.7,869.3,835.3
BEGIN DESCRIPTION:
Cross Section 3708.7
END DESCRIPTION:
XS GIS Cut Line= 5
      3148654.23     13903851.05      3148061.67     13903012.65
      3147727.57     13902792.02      3147424.99     13902804.63
      3146285.05      13902821.9
#Sta/Elev= 30
  3688.6    66.5  3798.6    64.4  3868.6    64.5  3998.6    62.7  4028.6    64.1
  4588.6    62.2  4658.6    60.1  4678.6    60.9  4755.3    60.5  4795.3    59.6
  4885.3      60  4915.3    59.3  4944.4   57.36  4977.2    58.1  4995.5   41.87
  4997.4    41.5  5004.5    41.9  5026.8   57.02  5045.1   57.82  5295.6    59.3
  5315.6    60.3  5385.6      59  5405.6    59.9  5478.5    60.7  5588.5    59.9
  5668.5    60.3  5708.5    59.8  5988.5    61.8  6138.5    61.1  6558.5    62.6
#Mann= 4 , 1 , 0
  3688.6      .2       0  3688.6     .14       0  4977.2    .045       0
  5026.8     .14       0
Bank Sta=4977.2,5026.8
XS Rating Curve= 0
Exp/Cntr=.3,.1

Type RM Length L Ch R = 1 ,2839.4  ,919.2,1105.4,1083.6
BEGIN DESCRIPTION:
Cross Section 2839.4
END DESCRIPTION:
XS GIS Cut Line= 4
      3148362.19     13902278.22      3148005.65     13901964.13
        3147778.     13902010.35      3146396.67     13902237.67
#Sta/Elev= 30
    4333    60.7    4423    59.8    4443    58.7    4483    59.1    4553    58.5
    4573    57.9  4808.2    56.9  4858.2    56.5  4938.2    57.6  4948.2    56.4
  4983.9   56.72  4995.5   41.78    4996   41.35  5000.8   41.09  5003.8   41.34
  5029.2   51.77  5070.7   57.28  5084.5   60.28  5090.4      57  5430.4      58
  5530.4    59.2  5710.4    59.1  5760.4    58.3  5820.4    59.2  5870.4    59.4
  5880.4    59.1  6010.4    60.1  6070.4      59  6130.4    59.1  6440.4    61.5
#Mann= 3 , 1 , 0
    4333     .14       0  4983.9    .045       0  5070.7     .14       0
Bank Sta=4983.9,5070.7
XS Rating Curve= 0
Exp/Cntr=.3,.1

Type RM Length L Ch R = 1 ,1734.0  ,994.7,1058.3,1043.4
BEGIN DESCRIPTION:
Cross Section 1734.0
END DESCRIPTION:
XS GIS Cut Line= 6
      3148336.72     13902176.35      3147929.25      13901217.1
      3147544.76     13901064.79      3146800.92     13901071.09
       3146596.5     13901268.04      3146392.76     13901641.55
#Sta/Elev= 30
  3367.7    60.5  3407.7    58.7  3467.7    58.9  3497.7    58.1  3627.7    57.6
  3647.7    57.1  3777.7    57.9  3907.7    57.2  3917.7    56.8  4429.9    54.7
  4589.9    55.2  4649.9    54.5  4923.5    55.2  4975.3   49.83  4983.5    48.6
  4993.5    45.5  4993.8   40.88  5002.8   39.65  5003.5    43.5  5013.5    44.7
  5031.9   51.64  5043.5    55.1  5063.5    55.4  5243.5    55.8  5428.9    56.9
  5448.9    57.7  5538.9    57.4  5567.3    57.8  6151.2    58.3  6276.7    59.6
#Mann= 3 , 1 , 0
  3367.7     .14       0  4975.3    .045       0  5031.9     .14       0
Bank Sta=4975.3,5031.9
XS Rating Curve= 0
Exp/Cntr=.3,.1

Type RM Length L Ch R = 1 ,675.7   ,0,0,0
BEGIN DESCRIPTION:
Cross Section 675.7
END DESCRIPTION:
XS GIS Cut Line= 6
      3148260.32     13901760.39      3147988.68     13900351.23
      3147790.61     13900097.16      3147172.84     13900071.95
      3147037.92     13900266.35       3146729.9     13901015.57
#Sta/Elev= 30
  2838.1    58.6  2958.1    56.9  3048.1    57.4  3658.1    54.7  3748.1    55.1
  3878.1    54.3  4248.1    54.1  4333.2    54.8  4433.2    53.8  4595.4    54.3
  4925.4    53.8  4932.6   54.95  4954.1   55.91  4962.9   59.31  4970.9   56.02
  4975.2   55.71  4993.7   40.23  5001.3   39.21  5004.9   39.27  5031.8   57.31
  5044.6   54.93  5062.6   55.21  5065.4    53.7  5115.4    53.9  5135.4    53.2
  5263.6    54.3  5450.3    54.1  5852.2   55.31  5908.4   55.74  6260.3    57.9
#Mann= 5 , 1 , 0
  2838.1     .14       0  4975.2    .045       0  5031.8     .14       0
  5852.2      .1       0  5908.4     .14       0
Bank Sta=4975.2,5031.8
XS Rating Curve= 0
Exp/Cntr=.3,.1

Chan Stop Cuts=-1